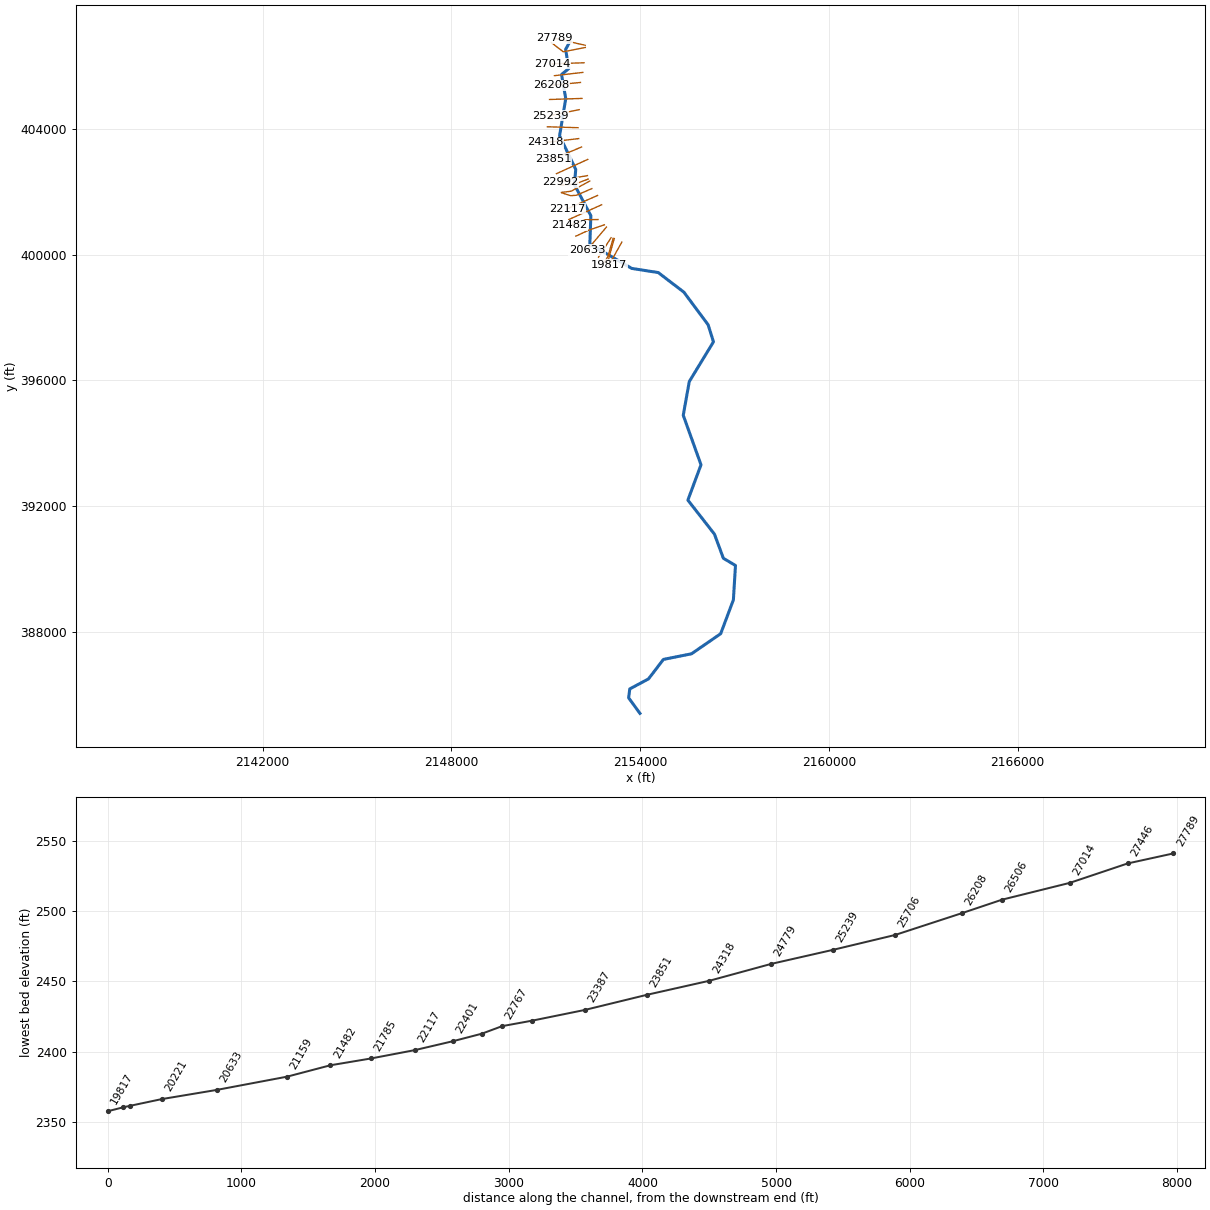
--- ROBBINSRN.prj (project) ---

Proj Title=ROBBINSRN
Current Plan=p01
Default Exp/Contr=0.3,0.1
English Units
Geom File=g01
Flow File=f01
Plan File=p01
Y Axis Title=Elevation
X Axis Title(PF)=Main Channel Distance
X Axis Title(XS)=Station
BEGIN DESCRIPTION:
Stream Name- Robbins Run
Flood Zone: Zone A
Greenbrier County, WV
County-Wide Study
WVDHSEM-2018-3, Flood Risk Project
HEC-RAS Version: 5.0.7
General Notes:
For the Hydrology Regression was used.
END DESCRIPTION:
DSS Export Rating Curves= 0
DSS Export Rating Curve Sorted= 0
DSS Export Volume Flow Curves= 0
DXF Filename=A3a.
DXF OffsetX= 0
DXF OffsetY= 0
DXF ScaleX= 1
DXF ScaleY= 10

--- ROBBINSRN.p01 (plan) ---

Plan Title=Floodplain
Program Version=5.07
Short Identifier=Floodplain
Geom File=g01
Flow File=f01
Subcritical Flow
K Sum by GR= 0
Std Step Tol= 0.01
Critical Tol= 0.01
Num of Std Step Trials= 20
Max Error Tol= 0.3
Flow Tol Ratio= 0.001
Split Flow NTrial= 30
Split Flow Tol= 0.02
Split Flow Ratio= 0.02
Log Output Level= 0
Friction Slope Method= 1
Unsteady Friction Slope Method= 2
Unsteady Bridges Friction Slope Method= 1
Parabolic Critical Depth
Global Vel Dist= 0 , 0 , 0
Global Log Level= 0
CheckData=True
Encroach Param=-1 ,0,0, 0
Computation Interval=1MIN
Output Interval=1HOUR
Instantaneous Interval=1HOUR
Mapping Interval=1HOUR
Computation Time Step Use Courant=        0
Computation Time Step Use Time Series=    0
Computation Time Step Count To Double=0
Computation Time Step Max Doubling=0
Computation Time Step Max Halving=0
Computation Time Step Residence Courant=0
Run HTab= 0
Run UNet= 0
Run Sediment= 0
Run PostProcess= 0
Run WQNet= 0
Run RASMapper= 0
UNET Theta= 1
UNET Theta Warmup= 1
UNET ZTol= 0.02
UNET ZSATol= 0.02
UNET MxIter= 20
UNET Max Iter WO Improvement= 0
UNET MaxInSteps= 0
UNET DtIC= 0
UNET DtMin= 0
UNET MaxCRTS= 20
UNET WFStab= 2
UNET SFStab= 1
UNET WFX= 1
UNET SFX= 1
UNET 1D Methodology=Finite Difference
UNET DSS MLevel= 4
UNET Pardiso=0
UNET DZMax Abort= 100
UNET Use Existing IB Tables=-1
UNET Froude Reduction=False
UNET Froude Limit= 0.8
UNET Froude Power= 4
UNET D1 Cores= 0
UNET D2 Coriolis=0
UNET D2 Cores= 0
UNET D2 Theta= 1
UNET D2 Theta Warmup= 1
UNET D2 Z Tol= 0.01
UNET D2 Volume Tol= 0.01
UNET D2 Max Iterations= 20
UNET D2 Equation= 0
UNET D2 RampUpFraction=0.1
UNET D2 TimeSlices= 1
UNET D2 BCVolumeCheck=0
UNET D1D2 MaxIter= 0
UNET D1D2 ZTol=0.01
UNET D1D2 QTol=0.1
UNET D1D2 MinQTol=1
Write IC File= 0
Write IC File at Fixed DateTime=0
Write IC File at Sim End=0
Echo Input=False
Echo Parameters=False
Echo Output=False
Write Detailed= 0
HDF Write Warmup=0
HDF Write Time Slices=0
HDF Flush=0
HDF Face Node Velocities=0
HDF Compression= 1
HDF Chunk Size= 1
HDF Spatial Parts= 1
HDF Use Max Rows=0
HDF Fixed Rows= 1
Calibration Method= 0
Calibration Iterations= 20
Calibration Max Change=0.05
Calibration Tolerance=0.2
Calibration Maximum=1.5
Calibration Minimum=0.5
Calibration Optimization Method= 1
WQ AD Non Conservative
WQ ULTIMATE=-1
WQ Max Comp Step=1HOUR
WQ Output Interval=15MIN
WQ Output Selected Increments= 0
WQ Output face flow=0
WQ Output face velocity=0
WQ Output face area=0
WQ Output face dispersion=0
WQ Output cell volume=0
WQ Output cell surface area=0
WQ Output cell continuity=0
WQ Output cumulative cell continuity=0
WQ Output face conc=0
WQ Output face dconc_dx=0
WQ Output face courant=0
WQ Output face peclet=0
WQ Output face adv mass=0
WQ Output face disp mass=0
WQ Output cell mass=0
WQ Output cell source sink temp=0
WQ Output nsm pathways=0
WQ Output nsm derived pathways=0
WQ Output MaxMinRange=-1
WQ Daily Max Min Mean=-1
WQ Daily Range=0
WQ Daily Time=0
WQ Create Restart=0
WQ Fixed Restart=0
WQ System Summary=0
WQ Write To DSS=0
WQ Use Fixed Temperature=0
Sorting and Armoring Iterations= 10
XS Update Threshold= 0.02
Bed Roughness Predictor= 0
Hydraulics Update Threshold= 0.02
Energy Slope Method= 1
Volume Change Method= 1
Sediment Retention Method= 0
XS Weighting Method= 0
Number of US Weighted Cross Sections= 1
Number of DS Weighted Cross Sections= 1
Upstream XS Weight=0
Main XS Weight=1
Downstream XS Weight=0
Number of DS XS's Weighted with US Boundary= 1
Upstream Boundary Weight= 1
Weight of XSs Associated with US Boundary= 0
Number of US XS's Weighted with DS Boundary= 1
Downstream Boundary Weight= 0.5
Weight of XSs Associated with DS Boundary= 0.5
Percentile Method= 0
Sediment Output Level= 3
Mass or Volume Output= 0
Output Increment Type= 1
Profile and TS Output Increment= 1
XS Output Flag= 0
XS Output Increment= 10
Write Gradation File= 0
Read Gradation Hotstart= 0
Write HDF5 File= 1
Write Binary Output= 1
Write DSS Sediment File= 0
SV Curve= 0
Specific Gage Flag= 0

--- ROBBINSRN.f01 (steady flow) ---

Flow Title=Flow
Program Version=5.07
Number of Profiles= 6
Profile Names=f1p,f10p,f4p,f2p,f02p,f1pplus
River Rch & RM=BEVERLYFK,Main            ,776
     323     167     225     272     456     478
River Rch & RM=BEVERLYFK,Main            ,220
     537     283     377     454     751     794
River Rch & RM=BOGGSRN,Main            ,1733
     558     295     392     472     780     825
River Rch & RM=DRYRN,Main            ,9301
     532     280     373     450     744     787
River Rch & RM=DRYRN,Main            ,8316
     594     314     418     503     829     878
River Rch & RM=DRYRN,Main            ,6862
     769     411     544     653    1070    1140
River Rch & RM=DRYRN,Main            ,5213
     898     483     637     763    1240    1330
River Rch & RM=DRYRN,Main            ,259
    1110     604     793     948    1540    1650
River Rch & RM=PNTHRCMPCK,Main            ,14558
     513     270     359     434     718     758
River Rch & RM=PNTHRCMPCK,Main            ,13060
     599     317     422     508     836     886
River Rch & RM=PNTHRCMPCK,Main            ,10150
     873     469     619     742    1210    1290
River Rch & RM=PNTHRCMPCK,Main            ,8160
     976     526     693     830    1350    1440
River Rch & RM=PNTHRCMPCK,Main            ,6420
    1080     588     772     923    1500    1600
River Rch & RM=RCKCMPRN,Main            ,4355
     581     307     409     492     812     860
River Rch & RM=RCKCMPRN,Main            ,1618
     692     368     488     586     963    1020
River Rch & RM=ROBBINSRN,Main            ,27789
     907     488     643     771    1260    1340
River Rch & RM=ROBBINSRN,Main            ,27014
    1170     638     837    1000    1620    1740
River Rch & RM=ROBBINSRN,Main            ,21785
    1330     728     953    1140    1830    1970
River Rch & RM=ROBBINSRN,Main            ,16781
    1830    1010    1320    1570    2500    2710
River Rch & RM=ROBBINSRN,Main            ,10962
    2050    1140    1480    1750    2790    3030
River Rch & RM=SPRINGCKT3,Main            ,6529
     583     309     410     494     815     863
River Rch & RM=SPRINGCKT3,Main            ,3093
     683     363     482     579     951    1010
River Rch & RM=SPRINGCKT3,Main            ,434
     860     462     609     730    1190    1270
Boundary for River Rch & Prof#=BEVERLYFK,Main            , 1
Up Type= 0
Dn Type= 3
Dn Slope=0.045649
Boundary for River Rch & Prof#=BEVERLYFK,Main            , 2
Up Type= 0
Dn Type= 3
Dn Slope=0.045649
Boundary for River Rch & Prof#=BEVERLYFK,Main            , 3
Up Type= 0
Dn Type= 3
Dn Slope=0.045649
Boundary for River Rch & Prof#=BEVERLYFK,Main            , 4
Up Type= 0
Dn Type= 3
Dn Slope=0.045649
Boundary for River Rch & Prof#=BEVERLYFK,Main            , 5
Up Type= 0
Dn Type= 3
Dn Slope=0.045649
Boundary for River Rch & Prof#=BEVERLYFK,Main            , 6
Up Type= 0
Dn Type= 3
Dn Slope=0.045649
Boundary for River Rch & Prof#=BOGGSRN,Main            , 1
Up Type= 0
Dn Type= 3
Dn Slope=0.043074
Boundary for River Rch & Prof#=BOGGSRN,Main            , 2
Up Type= 0
Dn Type= 3
Dn Slope=0.043074
Boundary for River Rch & Prof#=BOGGSRN,Main            , 3
Up Type= 0
Dn Type= 3
Dn Slope=0.043074
Boundary for River Rch & Prof#=BOGGSRN,Main            , 4
Up Type= 0
Dn Type= 3
Dn Slope=0.043074
Boundary for River Rch & Prof#=BOGGSRN,Main            , 5
Up Type= 0
Dn Type= 3
Dn Slope=0.043074
Boundary for River Rch & Prof#=BOGGSRN,Main            , 6
Up Type= 0
Dn Type= 3
Dn Slope=0.043074
Boundary for River Rch & Prof#=DRYRN,Main            , 1
Up Type= 0
Dn Type= 3
Dn Slope=0.021282
Boundary for River Rch & Prof#=DRYRN,Main            , 2
Up Type= 0
Dn Type= 3
Dn Slope=0.021282
Boundary for River Rch & Prof#=DRYRN,Main            , 3
Up Type= 0
Dn Type= 3
Dn Slope=0.021282
Boundary for River Rch & Prof#=DRYRN,Main            , 4
Up Type= 0
Dn Type= 3
Dn Slope=0.021282
Boundary for River Rch & Prof#=DRYRN,Main            , 5
Up Type= 0
Dn Type= 3
Dn Slope=0.021282
Boundary for River Rch & Prof#=DRYRN,Main            , 6
Up Type= 0
Dn Type= 3
Dn Slope=0.021282
Boundary for River Rch & Prof#=PNTHRCMPCK,Main            , 1
Up Type= 0
Dn Type= 3
Dn Slope=0.02712
Boundary for River Rch & Prof#=PNTHRCMPCK,Main            , 2
Up Type= 0
Dn Type= 3
Dn Slope=0.02712
Boundary for River Rch & Prof#=PNTHRCMPCK,Main            , 3
Up Type= 0
Dn Type= 3
Dn Slope=0.02712
Boundary for River Rch & Prof#=PNTHRCMPCK,Main            , 4
Up Type= 0
Dn Type= 3
Dn Slope=0.02712
Boundary for River Rch & Prof#=PNTHRCMPCK,Main            , 5
Up Type= 0
Dn Type= 3
Dn Slope=0.02712
Boundary for River Rch & Prof#=PNTHRCMPCK,Main            , 6
Up Type= 0
Dn Type= 3
Dn Slope=0.02712
Boundary for River Rch & Prof#=RCKCMPRN,Main            , 1
Up Type= 0
Dn Type= 3
Dn Slope=0.013802
Boundary for River Rch & Prof#=RCKCMPRN,Main            , 2
Up Type= 0
Dn Type= 3
Dn Slope=0.013802
Boundary for River Rch & Prof#=RCKCMPRN,Main            , 3
Up Type= 0
Dn Type= 3
Dn Slope=0.013802
Boundary for River Rch & Prof#=RCKCMPRN,Main            , 4
Up Type= 0
Dn Type= 3
Dn Slope=0.013802
Boundary for River Rch & Prof#=RCKCMPRN,Main            , 5
Up Type= 0
Dn Type= 3
Dn Slope=0.013802
Boundary for River Rch & Prof#=RCKCMPRN,Main            , 6
Up Type= 0
Dn Type= 3
Dn Slope=0.013802
Boundary for River Rch & Prof#=ROBBINSRN,Main            , 1
Up Type= 0
Dn Type= 3
Dn Slope=0.010317
Boundary for River Rch & Prof#=ROBBINSRN,Main            , 2
Up Type= 0
Dn Type= 3
Dn Slope=0.010317
Boundary for River Rch & Prof#=ROBBINSRN,Main            , 3
Up Type= 0
Dn Type= 3
Dn Slope=0.010317
Boundary for River Rch & Prof#=ROBBINSRN,Main            , 4
Up Type= 0
Dn Type= 3
Dn Slope=0.010317
Boundary for River Rch & Prof#=ROBBINSRN,Main            , 5
Up Type= 0
Dn Type= 3
Dn Slope=0.010317
Boundary for River Rch & Prof#=ROBBINSRN,Main            , 6
Up Type= 0
Dn Type= 3
Dn Slope=0.010317
Boundary for River Rch & Prof#=SPRINGCKT3,Main            , 1
Up Type= 0
Dn Type= 3
Dn Slope=0.016207
Boundary for River Rch & Prof#=SPRINGCKT3,Main            , 2
Up Type= 0
Dn Type= 3
Dn Slope=0.016207
Boundary for River Rch & Prof#=SPRINGCKT3,Main            , 3
Up Type= 0
Dn Type= 3
Dn Slope=0.016207
Boundary for River Rch & Prof#=SPRINGCKT3,Main            , 4
Up Type= 0
Dn Type= 3
Dn Slope=0.016207
Boundary for River Rch & Prof#=SPRINGCKT3,Main            , 5
Up Type= 0
Dn Type= 3
Dn Slope=0.016207
Boundary for River Rch & Prof#=SPRINGCKT3,Main            , 6
Up Type= 0
Dn Type= 3
Dn Slope=0.016207
DSS Import GetInterval= 0
DSS Import GetPeak= 0
DSS Import FillOption= 0

--- ROBBINSRN.g01 (geometry) ---

Geom Title=Geometry
Program Version=5.07

River Reach=ROBBINSRN       ,Main
Reach XY= 30
2151766.94998597 406773.892332122151631.63988914406528.632323949
2151731.99008213405918.9222572882151501.96003039405727.942324279
2151634.77013221404960.5823104512151439.46015538403779.162101118
2151952.71011314402710.5523616952151910.07010655402226.762318788
2152432.51984905401238.3620646132152401.26991156400338.192277028
2153732.86009614399561.2820854472154574.88006563399429.332218109
2155390.84989038398805.2022327762156161.68004164397767.012380032
2156330.07996731397225.3422035262155561.86004706395963.192168785
2155370.01987955394891.1421475392155934.25005031393314.752255706
2155516.72004548 392191.482192532156362.19998181 391109.02208711
2156645.18990138390341.662073283 2157029.7399853390113.362333028
2156963.76997289389019.6122239512156560.11986156387943.222316368
2155633.04002281387304.3321899462154738.94010498387125.512337623
 2154265.8498438386505.7222386142153670.35989305 386187.14216712
2153633.89999223385902.4222641122153993.24146514385409.231212556

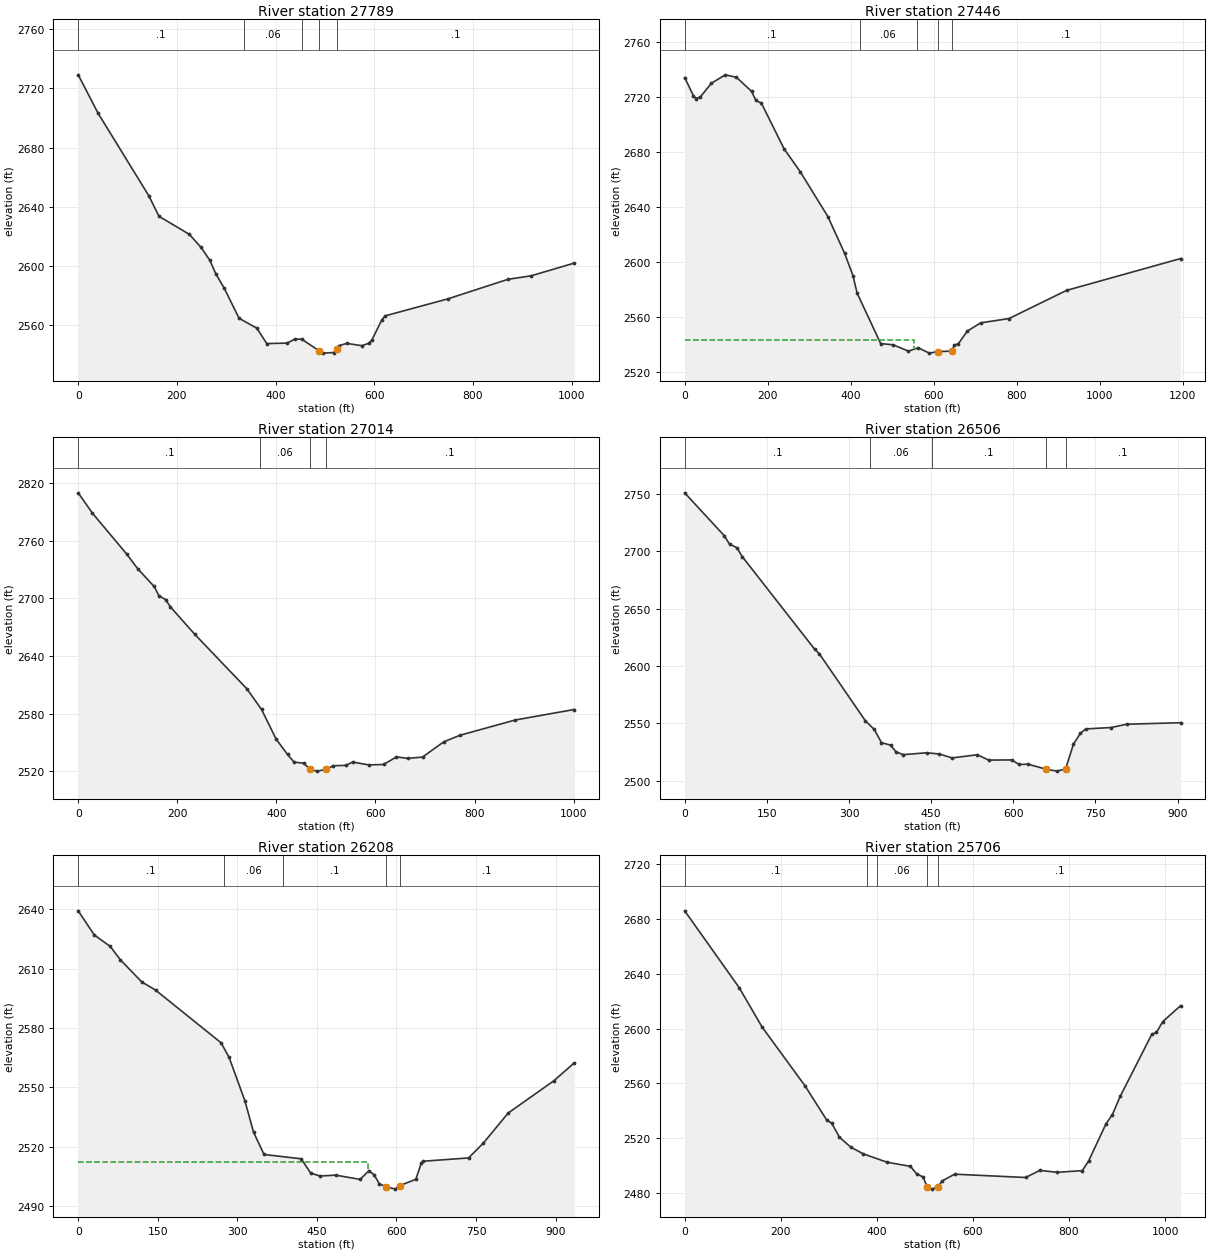
Type RM Length L Ch R = 1 ,27789   ,331.7,342.8,344.5
XS GIS Cut Line= 2
2152255.63798498406658.6375325622151274.88371289 406879.15447998
#Sta/Elev= 30
       0 2729.18    40.2 2703.27   143.2 2647.43   163.7 2633.62   225.1 2621.48
   248.7 2612.73   266.8  2603.9   278.9 2594.75   295.8 2585.16     326 2564.76
   362.1 2558.03   382.1 2547.66   423.3 2547.95   439.7 2550.78   453.5 2550.53
  487.89 2542.83   496.7  2541.2   517.7 2541.61   523.92543.693   527.8 2546.19
   544.6 2547.77   574.9 2546.24   588.9 2547.83     595 2549.87   615.2 2563.55
   621.9 2566.35     750 2577.93   870.8 2591.04   917.9 2593.43  1005.2 2601.99
#Mann= 5 ,-1 , 0
       0      .1       0  336.04     .06       0  453.89      .1       0
  487.89    .045       0   523.9      .1       0
Bank Sta=487.89,523.9
XS Rating Curve= 0 ,0
Exp/Cntr=0.3,0.1

Type RM Length L Ch R = 1 ,27446   ,428.9,432,426.3
XS GIS Cut Line= 3
2152256.72328463406588.1078179782151554.68335013406451.389259398
2151175.99414688 406745.44313322
#Sta/Elev= 30
       0 2734.09      21 2720.99    27.7 2718.89      38 2720.11    64.5 2730.02
    97.9 2736.09   124.7 2734.27   161.1 2724.14   171.4 2717.53   184.8 2715.55
   239.4 2682.39   278.4 2665.76   345.2 2633.04   385.3 2606.53   405.4 2590.34
   415.4 2577.59   472.2 2540.97   502.3 2540.08   539.1 2535.48   562.5 2537.96
   589.2 2534.04  610.722535.162  643.382535.512   649.4  2539.8   659.4 2540.89
   680.7 2549.98   712.9 2556.02   781.5 2559.16     920 2579.59  1194.7 2602.71
#Mann= 5 ,-1 , 0
       0      .1       0  421.88     .06       0  559.13      .1       0
  610.72    .045       0  643.38      .1       0
#XS Ineff= 2 , 0
          553.48 2543.34
Permanent Ineff=
       F       F
Bank Sta=610.72,643.38
XS Rating Curve= 0 ,0
Exp/Cntr=0.3,0.1

Type RM Length L Ch R = 1 ,27014   ,502,508,507.4
XS GIS Cut Line= 2
 2152218.7456703406101.9969135672151218.31164755 406068.35951364
#Sta/Elev= 30
       0 2809.59    28.6 2788.52    97.9 2745.87   120.5  2730.4   153.3 2712.21
   163.2 2702.34   176.3 2698.67   186.2 2690.91   235.4 2662.41   340.4 2605.84
     370 2584.43   399.5 2553.48   422.5 2537.56   435.6 2529.62   455.3  2528.5
  467.792522.178   482.2 2520.23   500.52521.956   514.4 2525.86   540.7 2526.18
   553.8 2529.71   586.6 2526.67   616.2 2527.16   642.4 2534.98   665.4  2533.5
     695 2534.84   737.6 2550.64   770.5 2557.52   882.1 2573.39    1001  2584.3
#Mann= 4 ,-1 , 0
       0      .1       0  367.67     .06       0  467.79    .045       0
   500.5      .1       0
Bank Sta=467.79,500.5
XS Rating Curve= 0 ,0
Exp/Cntr=0.3,0.1

Type RM Length L Ch R = 1 ,26506   ,298.5,297.8,296.9
XS GIS Cut Line= 2
2152176.42816964405794.9220683872151276.90536238405691.840581641
#Sta/Elev= 30
       0 2751.09    72.1 2713.75    81.9 2706.32    95.1 2703.27     105 2695.49
   237.1 2614.72   245.7 2610.73   329.6 2552.36   346.1 2544.58   359.3 2533.04
   375.8 2530.92   385.7 2525.04     399 2522.61   441.9 2524.23     465 2523.18
   488.1 2519.74   534.3 2522.53     555 2517.84   597.1 2518.01   610.3 2514.05
   626.8 2514.26  659.372509.985   679.5 2508.22  695.462510.153   709.7 2531.67
   722.6 2541.36   732.5 2545.06   778.7 2546.28   806.9 2549.15   905.4 2550.47
#Mann= 5 ,-1 , 0
       0      .1       0  338.93     .06       0  451.01      .1       0
  659.37    .045       0  695.46      .1       0
Bank Sta=659.37,695.46
XS Rating Curve= 0 ,0
Exp/Cntr=0.3,0.1

Type RM Length L Ch R = 1 ,26208   ,501.9,502.6,501.4
XS GIS Cut Line= 2
2152102.64321221405474.8265799732151171.65360439405389.106278971
#Sta/Elev= 30
       0  2639.1    30.3 2626.92    60.4 2621.14    79.3 2614.46   119.7 2603.24
   145.7 2599.14   269.4 2572.51   284.4 2565.16   314.1 2543.38   330.5 2527.44
   350.3 2516.18   420.2 2514.01   438.3 2506.77   455.7 2505.33   485.4 2505.74
   531.5 2503.61     548 2508.01   557.9 2505.92   567.7 2501.34  580.642499.957
   597.4  2498.7  605.792500.435   636.4 2503.64   646.8  2511.8   650.1 2512.77
   735.8 2514.43   763.4 2521.81   810.5 2537.08   896.9 2553.42   934.9 2562.33
#Mann= 5 ,-1 , 0
       0      .1       0  274.75     .06       0  386.32      .1       0
  580.64    .045       0  605.79      .1       0
#XS Ineff= 2 , 0
          546.12 2512.36
Permanent Ineff=
       F       F
Bank Sta=580.64,605.79
XS Rating Curve= 0 ,0
Exp/Cntr=0.3,0.1

Type RM Length L Ch R = 1 ,25706   ,464.9,466.3,467.4
XS GIS Cut Line= 2
2152151.29862672  404968.10876142151119.67404956404933.481534064
#Sta/Elev= 30
       0  2685.7   113.3 2629.85   161.3 2600.99     250 2558.51   295.9 2533.23
   305.8 2531.19   322.2 2520.85   345.2 2513.77   371.4 2508.79   421.3 2502.65
   469.9 2499.64     483 2494.08   496.2 2491.98  504.63 2484.77   515.1 2483.07
  527.662484.847   535.6    2489   561.8 2493.95   709.6 2491.54   739.1 2496.71
   775.2 2495.32   827.6 2496.52   840.9 2503.67     877 2530.72   890.1 2537.26
   906.5 2550.65   972.2  2595.8     982 2597.17   995.1 2605.07  1032.2 2616.67
#Mann= 5 ,-1 , 0
       0      .1       0  379.82      .1       0     401     .06       0
  504.63    .045       0  527.66      .1       0
Bank Sta=504.63,527.66
XS Rating Curve= 0 ,0
Exp/Cntr=0.3,0.1

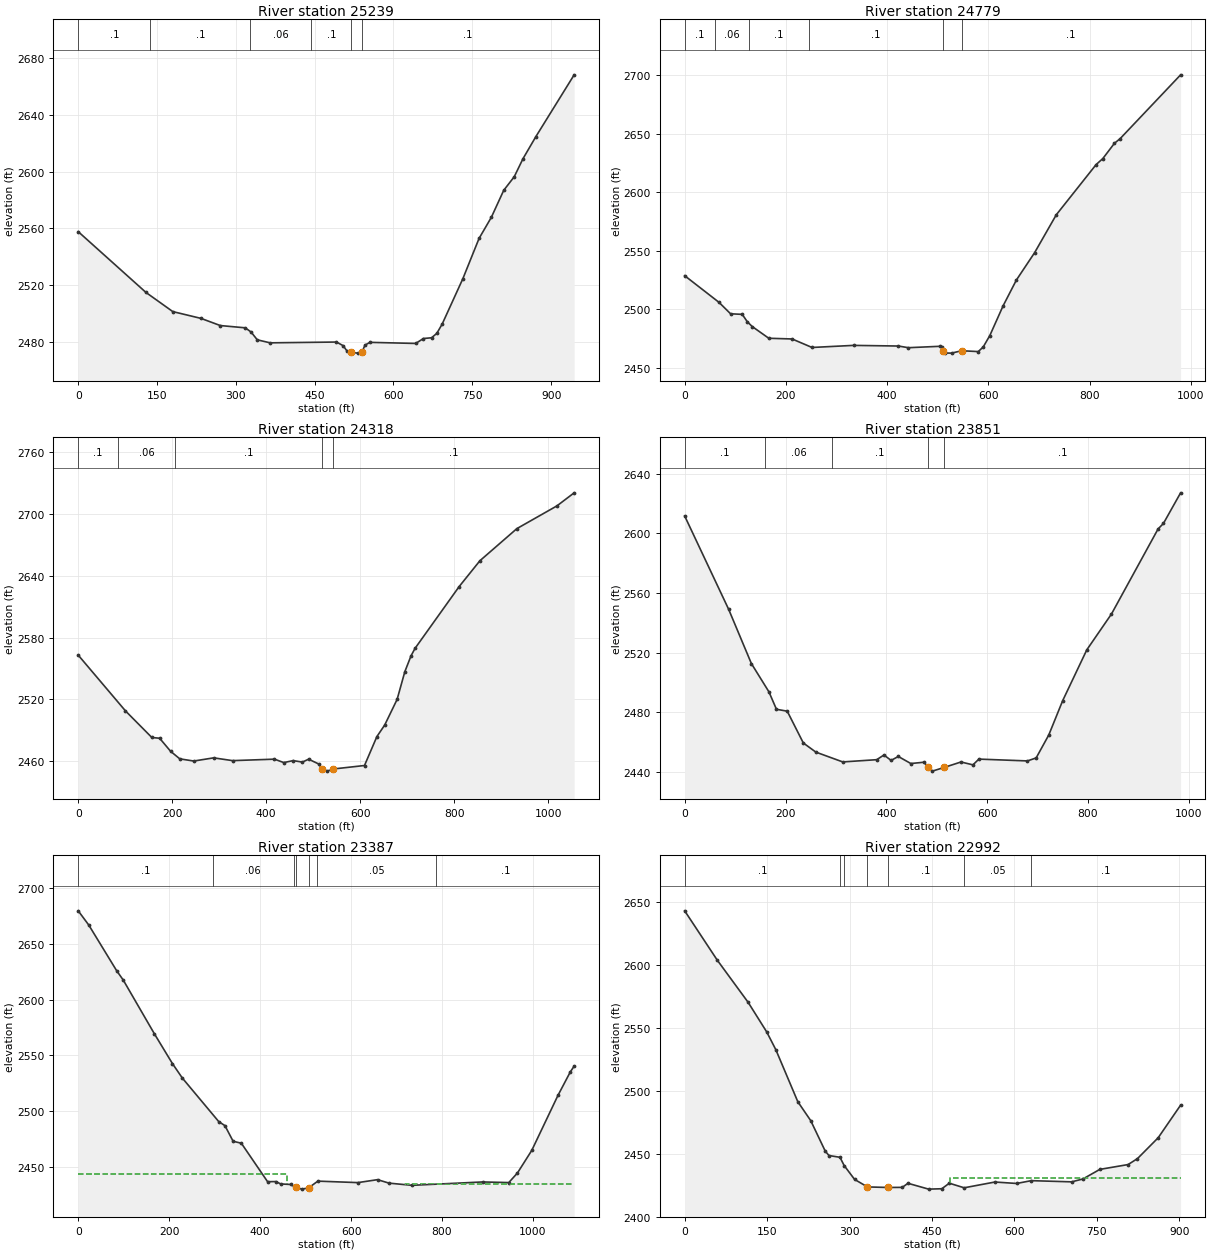
Type RM Length L Ch R = 1 ,25239   ,461.2,460.2,458.6
XS GIS Cut Line= 2
2152064.66592596404611.111443892 2151140.1868038404421.224356472
#Sta/Elev= 30
       0 2557.77     129 2515.05     180 2501.61   233.6 2496.85   270.4 2491.81
     318 2490.21     329 2487.24   340.8 2481.78   365.2 2479.67   491.5 2480.23
   504.2 2477.68   511.6 2473.89  520.022473.029   531.7 2472.44  540.052473.352
   545.8 2478.05   555.1 2480.01   642.2 2479.24     657 2482.71   672.4 2483.22
   682.4 2486.32   692.5 2492.74     732 2524.72   762.8 2552.99   786.2 2567.84
   809.8 2586.82   829.8 2596.35   846.5 2609.05   870.9  2624.5   943.8 2667.93
#Mann= 6 ,-1 , 0
       0      .1       0  137.54      .1       0  326.95     .06       0
  443.11      .1       0  520.02    .045       0  540.05      .1       0
Bank Sta=520.02,540.05
XS Rating Curve= 0 ,0
Exp/Cntr=0.3,0.1

Type RM Length L Ch R = 1 ,24779   ,456.5,461.8,461.5
XS GIS Cut Line= 2
2152028.25130063404037.0079333042151049.04098871404066.406496555
#Sta/Elev= 30
       0  2528.6    67.8 2505.85    90.7 2496.06   113.7 2495.59   123.6 2489.33
   133.4 2485.19   166.2 2475.17   212.2 2474.57   251.6 2467.31   333.6 2469.09
   422.3 2468.54   441.9 2467.12   504.3 2468.31   507.6 2467.57  511.122464.491
   514.2 2462.57   527.3 2462.48  547.162464.534   579.9 2463.79   589.7  2467.7
   602.8 2477.49     629 2502.84   655.3 2524.92   691.3 2548.27   734.1 2580.61
   812.8 2623.49     826 2628.59     849 2641.67   860.2 2645.61   979.7 2700.11
#Mann= 6 ,-1 , 0
       0      .1       0   60.73     .06       0  126.47      .1       0
  245.23      .1       0  511.12    .045       0  547.16      .1       0
Bank Sta=511.12,547.16
XS Rating Curve= 0 ,0
Exp/Cntr=0.3,0.1

Type RM Length L Ch R = 1 ,24318   ,461.5,466.9,468.6
XS GIS Cut Line= 2
 2152047.2853833403690.4521959722150999.02271606403567.119437397
#Sta/Elev= 30
       0 2563.05   100.6 2508.92   156.7 2483.12   173.3 2482.39   196.6 2469.74
   216.2 2462.39   245.9 2460.27   288.3 2463.36   328.5 2460.66   417.7 2462.09
   437.5 2458.77   457.4 2460.68   477.2 2459.27   490.4 2462.06   513.5 2457.05
  517.91 2452.66     530 2450.48  541.89 2452.49   609.3 2455.94   635.7 2484.03
   652.3 2495.21   678.7 2520.08   695.2 2547.06   708.4 2562.43   716.8 2569.58
   810.8 2629.62     855  2654.7   933.6 2685.83  1018.9  2707.9  1055.5 2720.56
#Mann= 5 ,-1 , 0
       0      .1       0   85.17     .06       0  206.22      .1       0
  517.91    .045       0  541.89      .1       0
Bank Sta=517.91,541.89
XS Rating Curve= 0 ,0
Exp/Cntr=0.3,0.1

Type RM Length L Ch R = 1 ,23851   ,462.5,463.8,463.9
XS GIS Cut Line= 2
2152138.45055531403422.960276887 2151230.2476473403045.356045231
#Sta/Elev= 30
       0 2611.53    87.3 2548.89   132.3 2512.59   167.1 2493.63     182 2481.94
   203.4 2480.67   235.3 2459.35   260.2 2453.22   313.5 2446.65   380.9 2448.15
   395.2 2451.29   409.4 2447.67   423.7  2450.3   448.5 2445.58   474.7 2446.45
  481.952443.449   491.2 2440.48  514.742442.958     548 2446.61   571.7 2444.69
   583.5 2448.54   679.8 2447.32   697.1 2449.34   722.1  2464.7   749.8  2487.8
   797.5 2521.77   846.5 2545.84   938.9 2602.84   949.5 2606.52   983.6 2627.05
#Mann= 5 ,-1 , 0
       0      .1       0  159.26     .06       0  293.15      .1       0
  481.95    .045       0  514.74      .1       0
#XS Ineff= 1 ,-1
  547.49  983.57 2446.47
Permanent Ineff=
       F
Bank Sta=481.95,514.74
XS Rating Curve= 0 ,0
Exp/Cntr=0.3,0.1

Type RM Length L Ch R = 1 ,23387   ,398.4,394.9,391.9
XS GIS Cut Line= 2
2152332.67818522403027.995187566 2151340.9245913402574.436055318
#Sta/Elev= 30
       0 2679.87    23.2  2667.1    84.5 2626.06      99 2617.66   167.3 2569.47
   207.2 2542.55   228.9 2529.58   308.9 2490.46   322.7 2486.74   340.6 2472.74
   358.7 2470.97   416.4 2436.39   434.7 2436.51   445.3 2434.36   466.9 2433.91
  478.142431.318   492.2 2429.71  506.782430.919     527  2436.9   614.9 2435.57
   658.2 2438.22   683.4  2435.1   733.9 2433.13   889.1 2436.16   946.8  2435.6
   965.8 2444.21   997.3 2464.53    1055 2514.05    1082 2535.03  1090.5 2540.29
#Mann= 7 ,-1 , 0
       0      .1       0  296.42     .06       0  473.57      .1       0
  478.14    .045       0  506.78      .1       0  524.21     .05       0
  787.63      .1       0
#XS Ineff= 2 , 0
           458.4 2443.72  719.55          2434.2
Permanent Ineff=
       F       F
Bank Sta=478.14,506.78
XS Rating Curve= 0 ,0
Exp/Cntr=0.3,0.1

Type RM Length L Ch R = 1 ,22992   ,224.9,224.8,232.4
XS GIS Cut Line= 3
2152323.96133913402513.4912953082151936.80857013402444.046880394
2151448.96144871402298.213510647
#Sta/Elev= 30
       0 2642.97    59.3 2603.81   115.5 2570.33   149.3 2546.84   165.9 2532.72
   205.9 2491.42   229.4 2476.42   255.9 2452.13   262.6 2448.74   282.6 2447.33
   290.2 2440.79   309.2 2429.77   332.6 2423.81   369.2 2423.38     396 2423.45
   406.3  2426.7   443.9 2422.06   467.9 2422.36   481.6 2426.76   508.6 2423.12
   564.6  2427.7   604.1 2426.55   630.7 2428.78   704.2 2427.84   724.7 2430.12
   755.5 2437.73   806.9 2441.56     824 2446.29   861.7 2462.86   902.5 2488.73
#Mann= 7 ,-1 , 0
       0      .1       0   282.6     .06       0   290.2      .1       0
   332.6    .045       0   369.2      .1       0   508.6     .05       0
   630.7      .1       0
#XS Ineff= 2 , 0
                          482.74         2431.09
Permanent Ineff=
       F       F
Bank Sta=332.6,369.2
XS Rating Curve= 0 ,0
Exp/Cntr=0.3,0.1

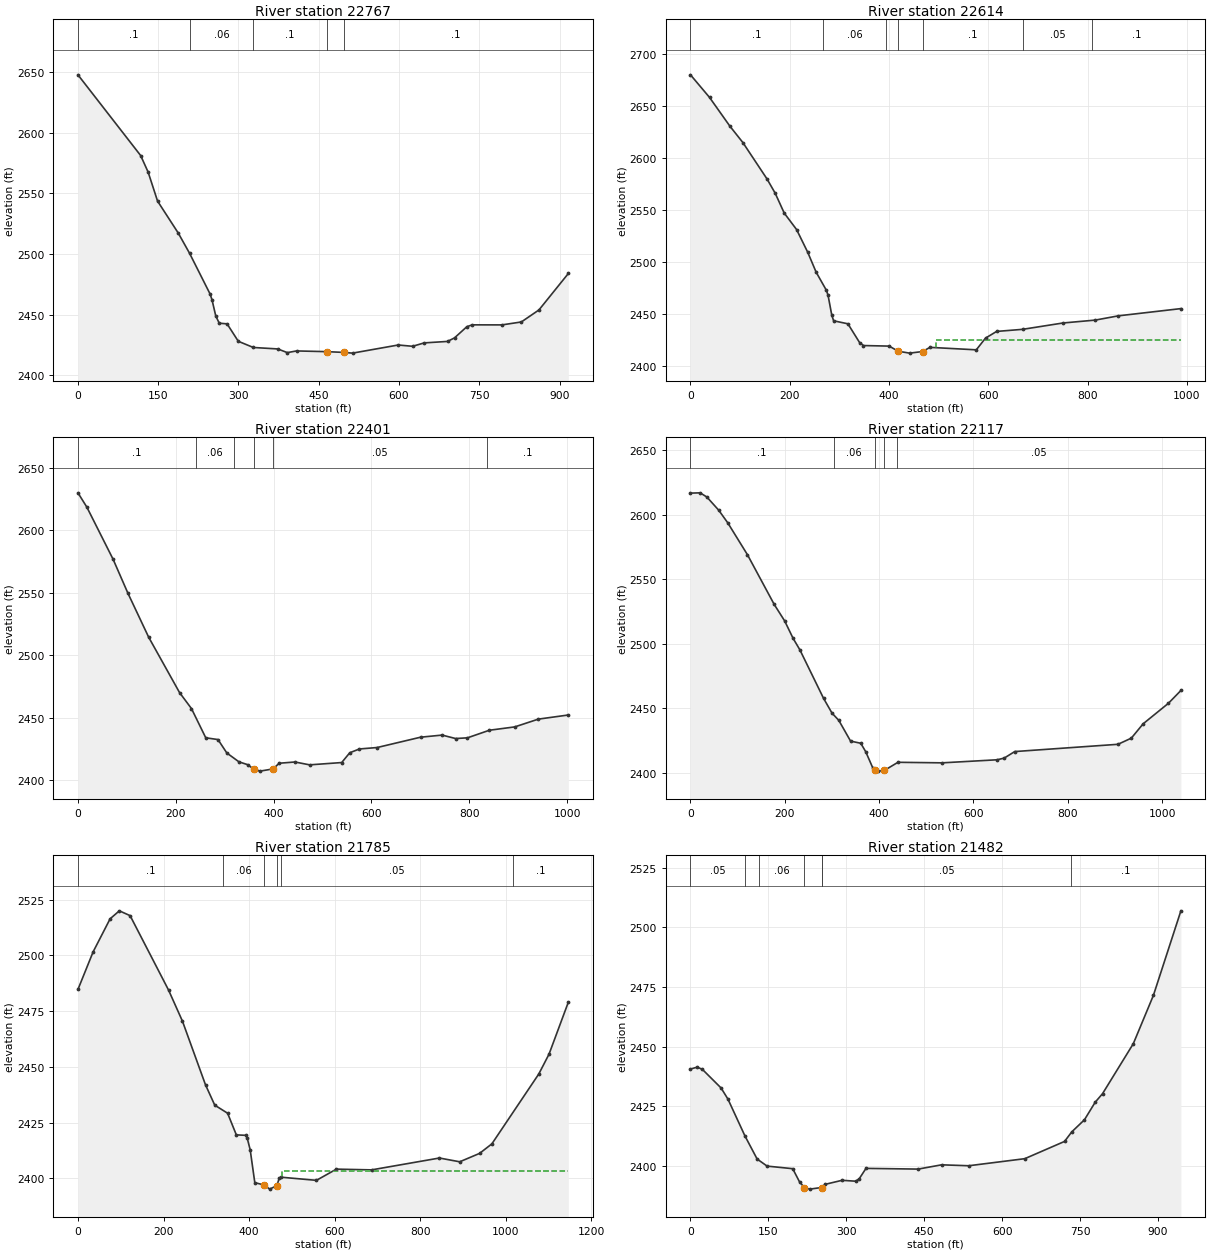
Type RM Length L Ch R = 1 ,22767   ,154.6,153,167.1
XS GIS Cut Line= 4
2152345.62649204402402.4440021652151927.02012856402243.123669796
  2151882.243826402238.9584323482151459.47222507402212.925698301
#Sta/Elev= 30
       0 2647.65   117.2 2581.09   131.2  2567.4   148.8 2543.51   187.4 2517.21
   208.5 2500.58   247.1 2466.76   250.6    2462   257.6 2448.75   264.1 2442.83
   278.7  2442.3   299.7 2427.91   327.8 2422.81   373.4  2421.6   391.3 2418.57
   408.5 2419.96   465.2 2419.36   496.6 2418.75   513.1 2418.15   598.5 2424.85
   625.4 2423.79   647.1 2426.59   690.6  2427.8   703.7 2430.72   726.7 2439.92
   736.6 2441.47   792.3 2441.43   828.6 2443.85   861.5 2453.77   916.4 2483.82
#Mann= 5 ,-1 , 0
       0      .1       0   208.5     .06       0   327.8      .1       0
   465.2    .045       0   496.6      .1       0
Bank Sta=465.2,496.6
XS Rating Curve= 0 ,0
Exp/Cntr(USF)=0,0
Exp/Cntr=0.3,0.1

Type RM Length L Ch R = 1 ,22614   ,213.5,212.9,210.3
XS GIS Cut Line= 3
2152401.03730047402341.1461675612151803.16415238402016.710464731
2151497.57257198401978.768939555
#Sta/Elev= 30
       0 2680.28    38.3  2658.6    79.4 2630.91   105.5  2615.2   154.1 2580.25
   170.7 2566.45   188.9 2547.35   213.8 2531.54   236.2 2509.73   253.2 2490.55
   273.9 2473.08   277.2 2468.35   284.7 2449.23   288.4 2443.83   317.2 2440.93
   340.7 2422.93   348.6 2420.03   400.4 2419.49   418.62414.554   441.5 2412.74
  467.662414.267   482.5 2418.29   575.9 2415.91   594.5 2427.17   616.9 2433.61
   669.2 2435.61   750.7 2441.72   815.9 2444.51   862.2 2448.59   988.2 2455.54
#Mann= 7 ,-1 , 0
       0      .1       0  267.69     .06       0  394.64      .1       0
   418.6    .045       0  467.66      .1       0  670.88     .05       0
  808.53      .1       0
#XS Ineff= 1 ,-1
  495.08  988.17 2424.99
Permanent Ineff=
       F
Bank Sta=418.6,467.66
XS Rating Curve= 0 ,0
Exp/Cntr=0.3,0.1

Type RM Length L Ch R = 1 ,22401   ,281.9,284.2,286.7
XS GIS Cut Line= 4
2152462.85016897402098.5606947242151976.73926455401888.491232976
2151789.23898339401874.6024812312151518.40586364401963.143970817
#Sta/Elev= 30
       0 2629.96    18.3 2618.47    71.9 2576.83   102.3 2549.59   144.7 2514.46
   207.7 2470.28   232.1 2457.47   261.3 2434.12   286.3 2432.71   304.4 2421.96
   329.2 2414.89   347.1 2412.62  359.582408.916   372.1 2407.47   398.82409.216
   411.4 2413.78   443.6 2414.77   473.6 2412.49   539.2 2414.33   555.7 2422.16
   575.4 2425.18   611.6 2426.34   700.4 2434.59   744.5 2436.28   772.1 2433.52
   796.3  2434.1   841.1 2440.16   892.9 2442.82   941.2 2449.04  1002.5 2452.35
#Mann= 6 ,-1 , 0
       0      .1       0   241.1     .06       0   319.1      .1       0
  359.58    .045       0   398.8     .05       0  835.48      .1       0
Bank Sta=359.58,398.8
XS Rating Curve= 0 ,0
Exp/Cntr=0.3,0.1

Type RM Length L Ch R = 1 ,22117   ,330.5,332.2,332.5
XS GIS Cut Line= 2
2152645.14179914401881.5466930572151693.75295389 401461.40809764
#Sta/Elev= 30
       0 2616.76    20.4 2616.99    34.7 2613.74    59.8 2603.54      79 2593.74
   120.8 2568.97   177.6 2530.39   199.7 2517.64   217.4 2504.25     232 2495.18
   282.1 2457.65   300.1 2446.13   314.5 2440.52   339.5 2424.41   361.1 2422.75
   371.7 2416.11   386.6 2403.62  390.872401.756   397.9 2401.13  410.87 2401.64
     440 2407.98   533.8 2407.56   650.3 2409.93   665.3 2411.24   687.6  2416.3
   906.6 2421.94   934.9 2426.72     960 2437.86  1013.6 2453.77    1040 2463.68
#Mann= 5 ,-1 , 0
       0      .1       0  303.41     .06       0  390.87    .045       0
  410.87     .06       0  437.71     .05       0
Bank Sta=390.87,410.87
XS Rating Curve= 0 ,0
Exp/Cntr=0.3,0.1

Type RM Length L Ch R = 1 ,21785   ,310.4,303,298.1
XS GIS Cut Line= 2
2152777.08641714401586.4078476432151731.94743131 401115.92191197
#Sta/Elev= 30
       0  2484.7    35.6 2501.63    75.2 2516.42    96.8    2520   121.9 2517.84
   211.9  2484.4   244.3 2470.47   298.2 2441.89   319.8 2432.78   349.8 2429.17
   370.2 2419.45   391.8 2419.25   395.4 2418.14   402.6 2412.76   413.4 2398.01
  435.542396.948   448.2  2395.1  465.012396.682   470.6 2400.11   475.5 2400.44
   557.4 2399.04   604.1 2404.07   686.4 2403.74   844.9 2409.06   892.3 2407.37
   938.7 2411.13   967.5 2415.42  1077.1 2446.76  1101.1 2455.68  1146.2    2479
#Mann= 6 ,-1 , 0
       0      .1       0  339.45     .06       0  435.54    .045       0
  465.01     .06       0  473.54     .05       0 1016.21      .1       0
#XS Ineff= 1 ,-1
   478.1 1146.15 2403.12
Permanent Ineff=
       F
Bank Sta=435.54,465.01
XS Rating Curve= 0 ,0
Exp/Cntr=0.3,0.1

Type RM Length L Ch R = 1 ,21482   ,315.3,322.9,328.2
XS GIS Cut Line= 3
2152662.50298488 401115.921911972152259.72524714401110.713589057
2151749.30861706400930.157847807
#Sta/Elev= 30
       0 2440.61      13  2441.4    22.9 2440.46    58.9 2432.66    72.1    2428
   104.9 2412.53   128.3 2402.88   147.5 2399.91   196.8 2398.83   209.9 2393.32
  219.422390.888   229.6 2390.26  252.262390.933   259.1 2392.26   291.9 2393.96
   318.2 2393.58     325 2394.65   337.9 2398.96   438.3 2398.66   483.5 2400.45
   535.7 2400.06   643.6 2403.02   720.2 2410.26   734.1 2414.26   758.5 2419.33
   779.3 2426.73   793.3 2430.26   852.6 2451.24   891.2 2471.44   944.2 2506.93
#Mann= 7 ,-1 , 0
       0     .05       0  104.79      .1       0  131.02     .06       0
  219.42    .045       0  252.26     .06       0  253.72     .05       0
  733.17      .1       0
Bank Sta=219.42,252.26
XS Rating Curve= 0 ,0
Exp/Cntr=0.3,0.1

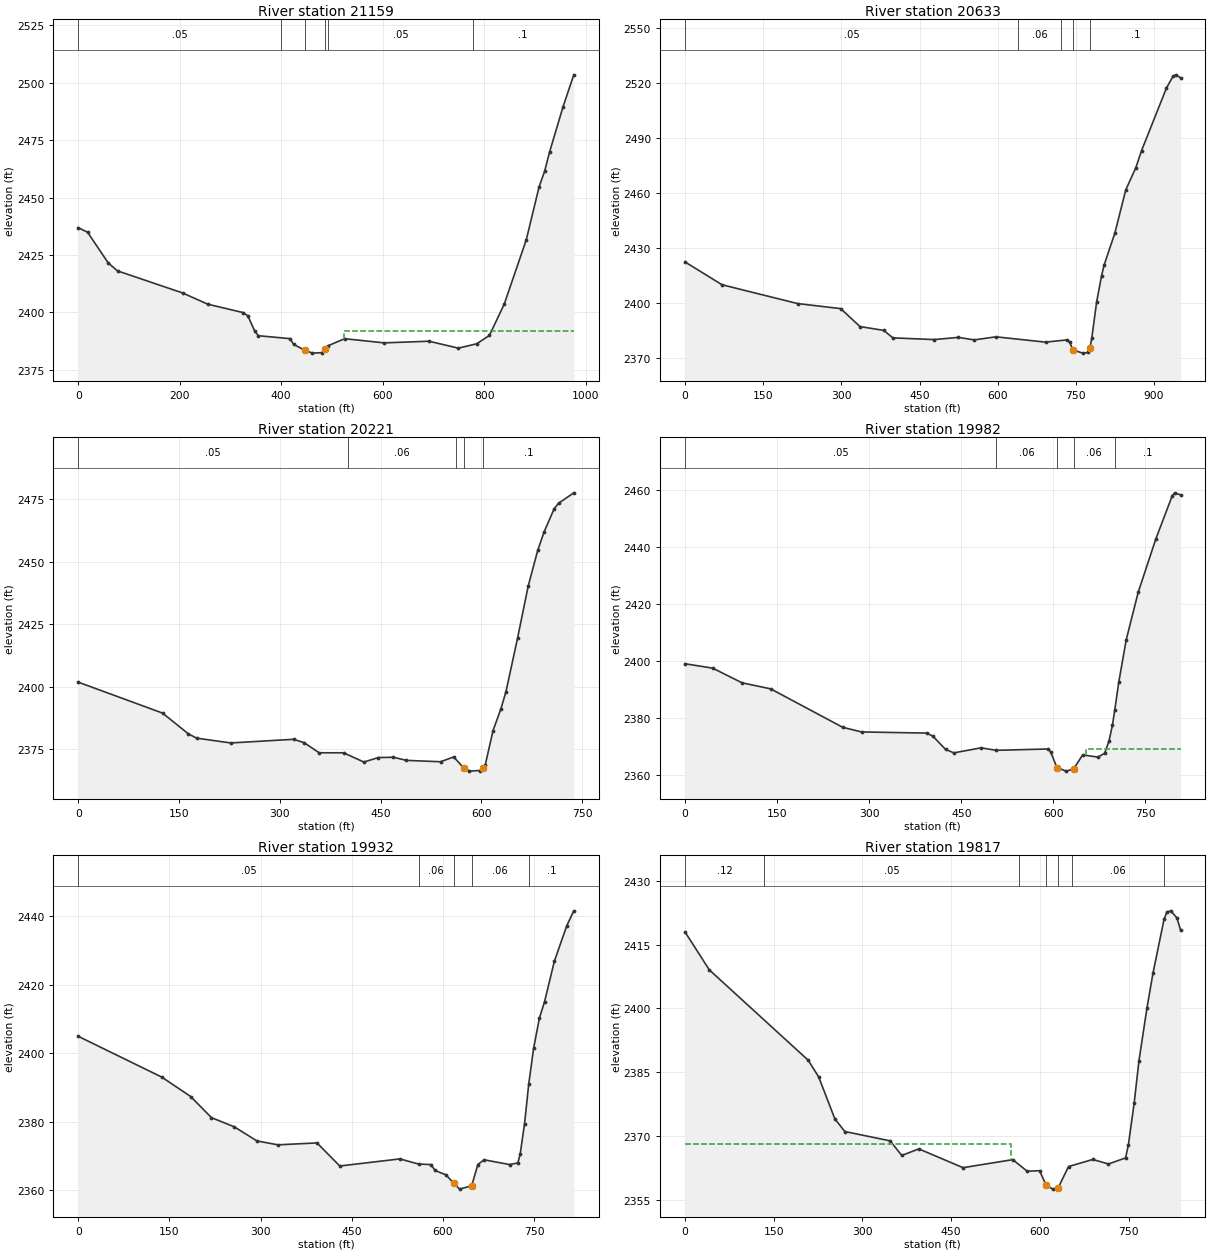
Type RM Length L Ch R = 1 ,21159   ,520.8,526.3,535.8
XS GIS Cut Line= 3
 2152863.8920178400949.2552505582152360.41959955400775.644049227
2151957.64186181400588.144096151
#Sta/Elev= 30
       0 2436.86    18.6 2434.85    59.1 2421.51    77.6 2418.01     206 2408.39
   255.2 2403.51   324.9 2399.85   334.4 2398.44   348.1  2391.7   355.2 2389.76
   417.7 2388.48   424.6 2385.97  447.622383.329   461.7 2382.17   480.1 2382.37
  486.822384.038   492.7 2385.41   525.2 2388.46     603 2386.64   691.4 2387.36
   749.3 2384.34   785.5 2386.25   810.5 2389.89   839.8 2403.57   883.2 2431.61
   908.5 2454.71   919.4  2461.5     929 2469.79   955.6 2489.53   976.8 2503.49
#Mann= 6 ,-1 , 0
       0     .05       0  399.74     .06       0  447.62    .045       0
  486.82     .06       0   492.7     .05       0  777.26      .1       0
#XS Ineff= 2 , 0
                          524.05         2391.96
Permanent Ineff=
       F       F
Bank Sta=447.62,486.82
XS Rating Curve= 0 ,0
Exp/Cntr=0.3,0.1

Type RM Length L Ch R = 1 ,20633   ,409.1,411.6,412.6
XS GIS Cut Line= 2
 2152928.1281098400876.338401645 2152315.2809103400148.908097982
#Sta/Elev= 30
       0 2422.51    70.9 2410.06   215.9 2399.78   298.7 2397.02   335.7 2387.23
   381.5 2385.12   398.8 2381.05   478.3 2380.12   524.8 2381.32   554.9 2379.94
   596.7 2381.62     692 2378.72   732.9 2379.94     738 2378.75  744.542374.439
   763.4 2372.72   773.6 2373.09  777.342375.578   780.6 2380.81   789.9  2400.5
   799.4 2414.89   804.2 2420.69   824.9 2438.19   845.8 2461.77   865.3 2474.02
   876.1 2483.21   923.8 2517.31   936.6 2523.91   941.7 2524.66   951.2 2523.05
#Mann= 5 ,-1 , 0
       0     .05       0  638.57     .06       0  722.53      .1       0
  744.54    .045       0  777.34      .1       0
Bank Sta=744.54,777.34
XS Rating Curve= 0 ,0
Exp/Cntr=0.3,0.1

Type RM Length L Ch R = 1 ,20221   ,237.6,239.2,241.3
XS GIS Cut Line= 2
2153075.69736847400537.7967558952152676.39173664399918.005016476
#Sta/Elev= 30
       0 2401.76   125.5 2389.39   163.9 2381.09   176.2 2379.37   226.9 2377.45
   320.6 2378.91   336.2 2377.53   358.5 2373.52   394.8 2373.51     425 2369.81
   446.4  2371.6   468.9 2371.73   488.4 2370.48   539.2 2369.93   558.7 2371.86
  573.442367.472   582.1 2366.18   597.7 2366.43  602.93 2367.49   605.5 2368.56
   617.2  2382.4   628.9 2391.11   636.3 2397.84   653.7 2419.41   669.5 2440.19
   683.7 2454.49   693.2 2461.88   708.2 2471.14   714.6 2473.27   737.3 2477.46
#Mann= 5 ,-1 , 0
       0     .05       0  401.63     .06       0  561.77      .1       0
  573.44    .045       0  602.93      .1       0
#XS Ineff= 2 , 0
          558.48 2371.83
Permanent Ineff=
       F       F
Bank Sta=573.44,602.93
XS Rating Curve= 0 ,0
Exp/Cntr=0.5,0.3

Type RM Length L Ch R = 1 ,19982   ,46.7,50,54.1
XS GIS Cut Line= 5
2153141.49849931400518.3248389082153098.80481547400368.376290796
2152976.97162013399950.8112366782152949.89757673399893.539221774
2152867.63413714  399764.4168609
#Sta/Elev= 30
       0 2399.03    45.1 2397.48    92.8 2392.34   139.5 2390.22   256.8 2376.73
   287.5  2375.1   393.5  2374.7   403.7 2373.62   424.3 2368.98   437.9 2367.76
   482.3 2369.53   506.7 2368.65   590.9 2369.12   595.4 2368.18   605.8 2362.59
   620.8 2361.35   632.9 2362.09   647.7 2367.03   672.8 2366.27   683.6 2367.65
   690.7 2372.02   696.2 2377.46   700.1 2382.93   706.5 2392.54   718.7  2407.5
   738.2 2424.13   766.7 2442.71   793.4 2457.86   797.6 2459.01   807.3 2458.27
#Mann= 5 ,-1 , 0
       0     .05       0   506.7     .06       0   605.8    .045       0
   632.9     .06       0   700.1      .1       0
#XS Ineff= 2 , 0
           585.8    2369   652.9            2369
Permanent Ineff=
       F       F
Bank Sta=605.8,632.9
XS Rating Curve= 0 ,0
Exp/Cntr(USF)=0,0
Exp/Cntr=0.5,0.3

Type RM Length L Ch R = 1 ,19932   ,118.9,114.9,110.6
XS GIS Cut Line= 4
2153177.94432698400512.0769827362153016.54137589399937.274214974
2153005.08697291399877.9195813462152935.31924566399736.301508129
#Sta/Elev= 30
       0 2404.92   137.4 2393.02   185.1 2387.34   219.3 2381.17   256.6 2378.52
   294.1 2374.38   328.5 2373.25   392.9  2373.8   430.4 2367.07   529.3 2369.14
   560.2 2367.63   580.4 2367.49   587.2 2365.76   605.4 2364.46   617.5 2362.09
   627.5 2360.32   647.4 2361.29   657.6  2367.5   667.8 2368.88   709.9 2367.49
   723.4 2367.97   727.2 2370.52   734.4 2379.38   741.3 2391.03   749.4 2401.51
   758.9 2410.27   767.3    2415   783.4 2426.79   803.8 2437.15   815.4 2441.53
#Mann= 5 ,-1 , 0
       0     .05       0   560.2     .06       0   617.5    .045       0
   647.4     .06       0   741.3      .1       0
Bank Sta=617.5,647.4
XS Rating Curve= 0 ,0
Exp/Cntr(USF)=0,0
Exp/Cntr=0.5,0.3

Type RM Length L Ch R = 1 ,19817   ,459.1,459.5,460.1
XS GIS Cut Line= 2
2153419.44733714 400400.644143062153009.72538756399669.741405398
#Sta/Elev= 30
       0 2417.95      41 2409.05   208.2 2387.82     226 2383.88   253.1 2374.09
     270 2371.07   346.8 2368.87   366.4 2365.44   395.3 2366.98     470 2362.57
   554.2 2364.46   578.5 2361.73   599.3 2361.86   610.6 2358.46   621.9 2357.53
  630.762357.811   648.4 2362.84   689.4  2364.5   715.9 2363.44   744.8 2364.86
   749.6 2367.95   759.3 2377.71   767.4 2387.66   780.9 2400.02   791.1 2408.24
   809.9 2420.95   814.7 2422.63   821.2 2422.92   831.6 2421.27   837.9 2418.34
#Mann= 7 ,-1 , 0
       0     .12       0  134.17     .05       0     565      .1       0
   610.6    .045       0  630.76      .1       0  654.43     .06       0
     810      .1       0
#XS Ineff= 2 , 0
          550.65 2368.09   686.8         2363.78
Permanent Ineff=
       F       F
Bank Sta=610.6,630.76
XS Rating Curve= 0 ,0
Exp/Cntr=0.3,0.1