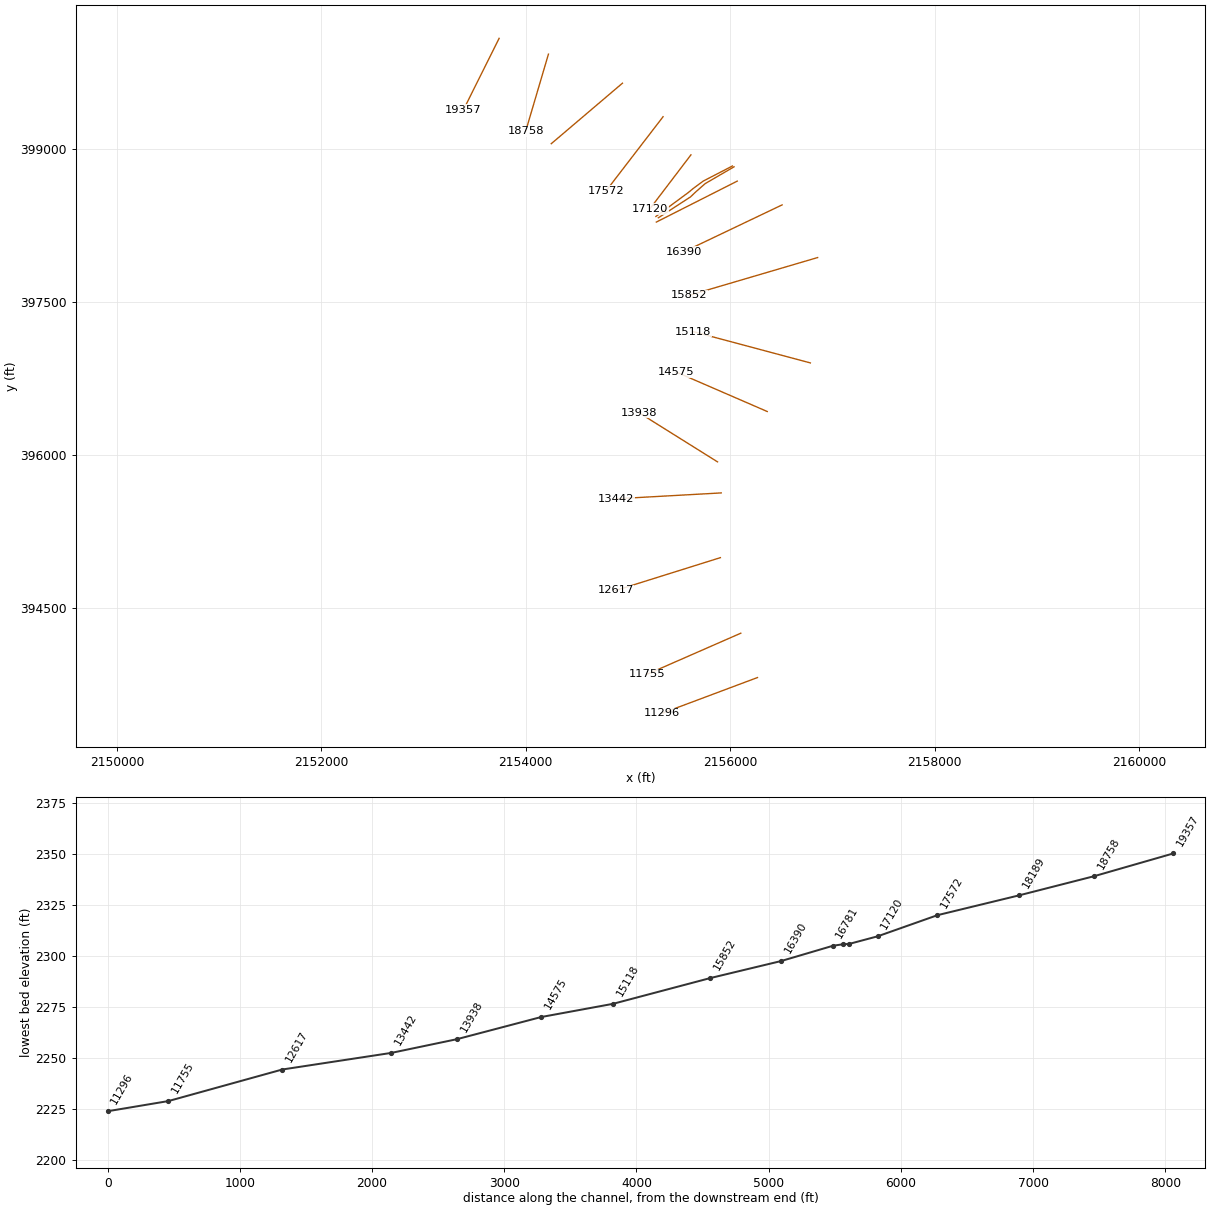
HEC-RAS study ROBBINSRN.prj: ROBBINSRN

--- ROBBINSRN.g01 (geometry) --- (continued)

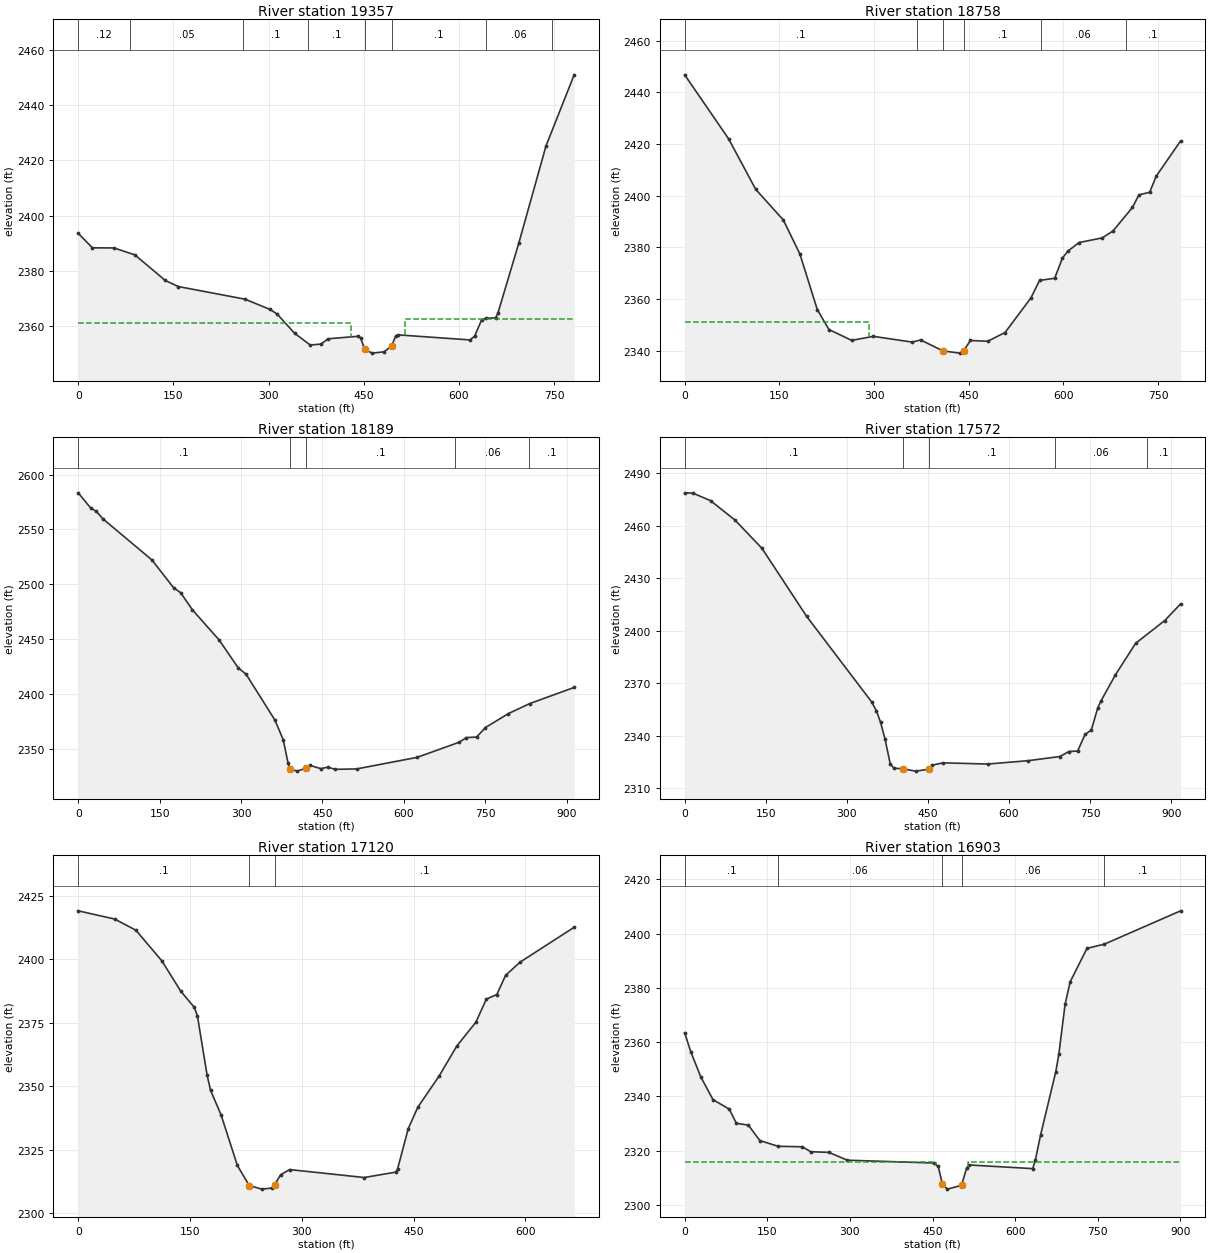
Type RM Length L Ch R = 1 ,19357   ,597.2,599.8,604.7
XS GIS Cut Line= 2
2153738.89190821400079.4633549752153389.93361664399379.810882896
#Sta/Elev= 30
       0 2393.59    22.4 2388.35    56.6 2388.29    89.3  2385.8   137.3 2376.52
   157.8 2374.33     263 2369.75   302.3 2366.04   313.3 2364.43   341.2  2357.4
   365.7 2353.16   382.8  2353.5   393.9 2355.41   441.4 2356.32   445.3 2355.71
  451.44 2351.56   463.6 2350.22   481.9 2350.69  493.972352.703   500.2 2356.31
   503.9 2356.84   617.6    2355   624.9 2356.37   635.9 2362.23   643.2 2362.86
   657.9 2362.98   661.6 2364.69   694.6 2390.08   737.5 2425.29   781.8 2450.98
#Mann= 8 ,-1 , 0
       0     .12       0   82.28     .05       0  259.86      .1       0
  362.19      .1       0  451.44    .045       0  493.97      .1       0
   643.2     .06       0  746.23      .1       0
#XS Ineff= 2 , 0
          430.55 2361.26  515.51         2362.65
Permanent Ineff=
       F       F
Bank Sta=451.44,493.97
XS Rating Curve= 0 ,0
Exp/Cntr=0.3,0.1

Type RM Length L Ch R = 1 ,18758   ,576.2,568.7,559.8
XS GIS Cut Line= 2
2154221.53070672399924.9495563952153999.30871022399171.477310061
#Sta/Elev= 30
       0 2446.73    69.6 2421.96   112.5 2402.43   156.2 2390.58   182.5 2377.41
     210 2355.92   228.5 2348.17   264.6 2343.97   298.8 2345.54   360.4  2343.3
   373.8 2344.14  409.152339.895   435.6 2339.04  441.882339.968   452.7 2343.93
   480.1 2343.64   507.5 2347.02   548.5 2360.41   562.2 2367.18   586.1 2368.01
   598.3 2375.77   606.6 2378.42   624.7 2381.83   661.4 2383.63   678.5 2386.32
   709.3  2395.4   719.5 2400.27   736.6  2401.3   746.9 2407.48   785.6 2421.17
#Mann= 6 ,-1 , 0
       0      .1       0  367.48      .1       0  409.15    .045       0
  441.88      .1       0  564.23     .06       0  698.33      .1       0
#XS Ineff= 2 , 0
          292.47 2350.95
Permanent Ineff=
       F       F
Bank Sta=409.15,441.88
XS Rating Curve= 0 ,0
Exp/Cntr=0.3,0.1

Type RM Length L Ch R = 1 ,18189   ,610.9,616.5,619
XS GIS Cut Line= 2
2154945.48923256399640.227356806 2154249.3085383399048.213448972
#Sta/Elev= 30
       0 2583.37    23.1 2569.46    33.3 2566.55    45.1 2559.83   135.9 2522.15
   175.8 2496.79   188.7 2492.35   210.5 2476.64   259.3 2449.43     295 2423.69
   309.3 2418.02   362.5 2376.15   377.7 2358.34   386.8  2336.8  389.782331.771
   403.6 2329.62  419.262332.195   426.8 2334.89   447.1 2331.89     460 2333.25
   473.4 2331.25     513 2331.63   624.7 2342.19   701.8 2355.92   715.4 2360.22
   734.1 2360.68   750.4 2369.35   792.9 2382.11   831.8 2391.16   913.9 2405.93
#Mann= 5 ,-1 , 0
       0      .1       0  389.78    .045       0  419.26      .1       0
  695.12     .06       0  831.38      .1       0
Bank Sta=389.78,419.26
XS Rating Curve= 0 ,0
Exp/Cntr=0.3,0.1

Type RM Length L Ch R = 1 ,17572   ,450.2,452.3,452.5
XS GIS Cut Line= 2
2155343.05864739399312.1023568962154784.03089406398584.671725139
#Sta/Elev= 30
       0 2478.94    15.3 2478.77    47.8 2474.46    93.3 2463.31     143  2447.2
   225.7 2408.31   345.7 2359.53   354.6 2354.39   362.3 2347.87   370.6 2338.24
   380.3    2324   387.1 2321.58  403.012321.265   427.1 2319.91  452.162321.016
   457.5 2323.32   478.1 2324.64   560.5 2323.96   635.4 2325.88   693.9 2328.25
   710.7 2331.11   726.9  2331.4   740.6 2340.85   752.3 2343.47     764 2355.92
   769.9 2359.92   796.8 2374.94   834.2 2392.95   888.1 2405.98   917.4 2415.49
#Mann= 5 ,-1 , 0
       0      .1       0  403.01    .045       0  452.16      .1       0
  685.56     .06       0  854.38      .1       0
Bank Sta=403.01,452.16
XS Rating Curve= 0 ,0
Exp/Cntr=0.3,0.1

Type RM Length L Ch R = 1 ,17120   ,220,217.2,213.7
XS GIS Cut Line= 2
2155615.62798414398938.8386677212155212.85024638398409.324634895
#Sta/Elev= 30
       0    2419    48.9 2415.77    77.4 2411.37   112.1 2399.37   137.8 2387.29
   155.8 2381.02   159.9  2377.7   172.9 2354.36   177.6 2348.37   191.7 2338.69
   213.5 2318.86  229.412310.945   246.4 2309.54   259.6 2309.95  263.752311.335
   271.4 2315.16   283.5 2317.23   383.7 2314.11   425.8 2316.22   428.5 2317.54
   442.7 2333.29   455.6 2341.76   484.3 2354.08   507.7 2365.73   533.5 2375.22
   547.5 2384.27   561.6 2386.09   573.3 2393.61   592.7 2398.81   665.3 2412.53
#Mann= 3 ,-1 , 0
       0      .1       0  229.41    .045       0  263.75      .1       0
#XS Ineff= 1 ,-1
   298.7  665.29 2315.98
Permanent Ineff=
       F
Bank Sta=229.41,263.75
XS Rating Curve= 0 ,0
Exp/Cntr=0.5,0.3

Type RM Length L Ch R = 1 ,16903   ,44,45.6,52.2
XS GIS Cut Line= 5
2156021.91655297398830.0063159622155735.73037712398681.978983623
2155640.08194699398611.381332815 2155588.4621593398568.870919425
2155272.67051698398335.822760306
#Sta/Elev= 30
       0 2363.41      11 2356.48    29.2 2347.19    51.4 2338.76      81 2335.27
    93.8 2330.06   115.7 2329.37   136.4  2323.7   169.6 2321.57   213.9  2321.4
   228.7 2319.57   261.8 2319.34   295.2 2316.45   451.9 2315.41   460.4 2314.13
   467.9 2307.59   477.1 2305.78   502.6 2307.19   512.2 2313.74   516.9 2314.68
   631.9 2313.34   636.6 2316.42   646.2 2325.77   673.8 2349.09   679.3 2355.51
   690.6 2373.89   699.9 2382.24   730.4 2394.56   762.2 2396.13   900.4  2408.4
#Mann= 5 ,-1 , 0
       0      .1       0   169.6     .06       0   467.9    .045       0
   502.6     .06       0   762.2      .1       0
#XS Ineff= 2 , 0
             457  2315.8     514          2315.8
Permanent Ineff=
       F       F
Bank Sta=467.9,502.6
XS Rating Curve= 0 ,0
Exp/Cntr(USF)=0,0
Exp/Cntr=0.5,0.3

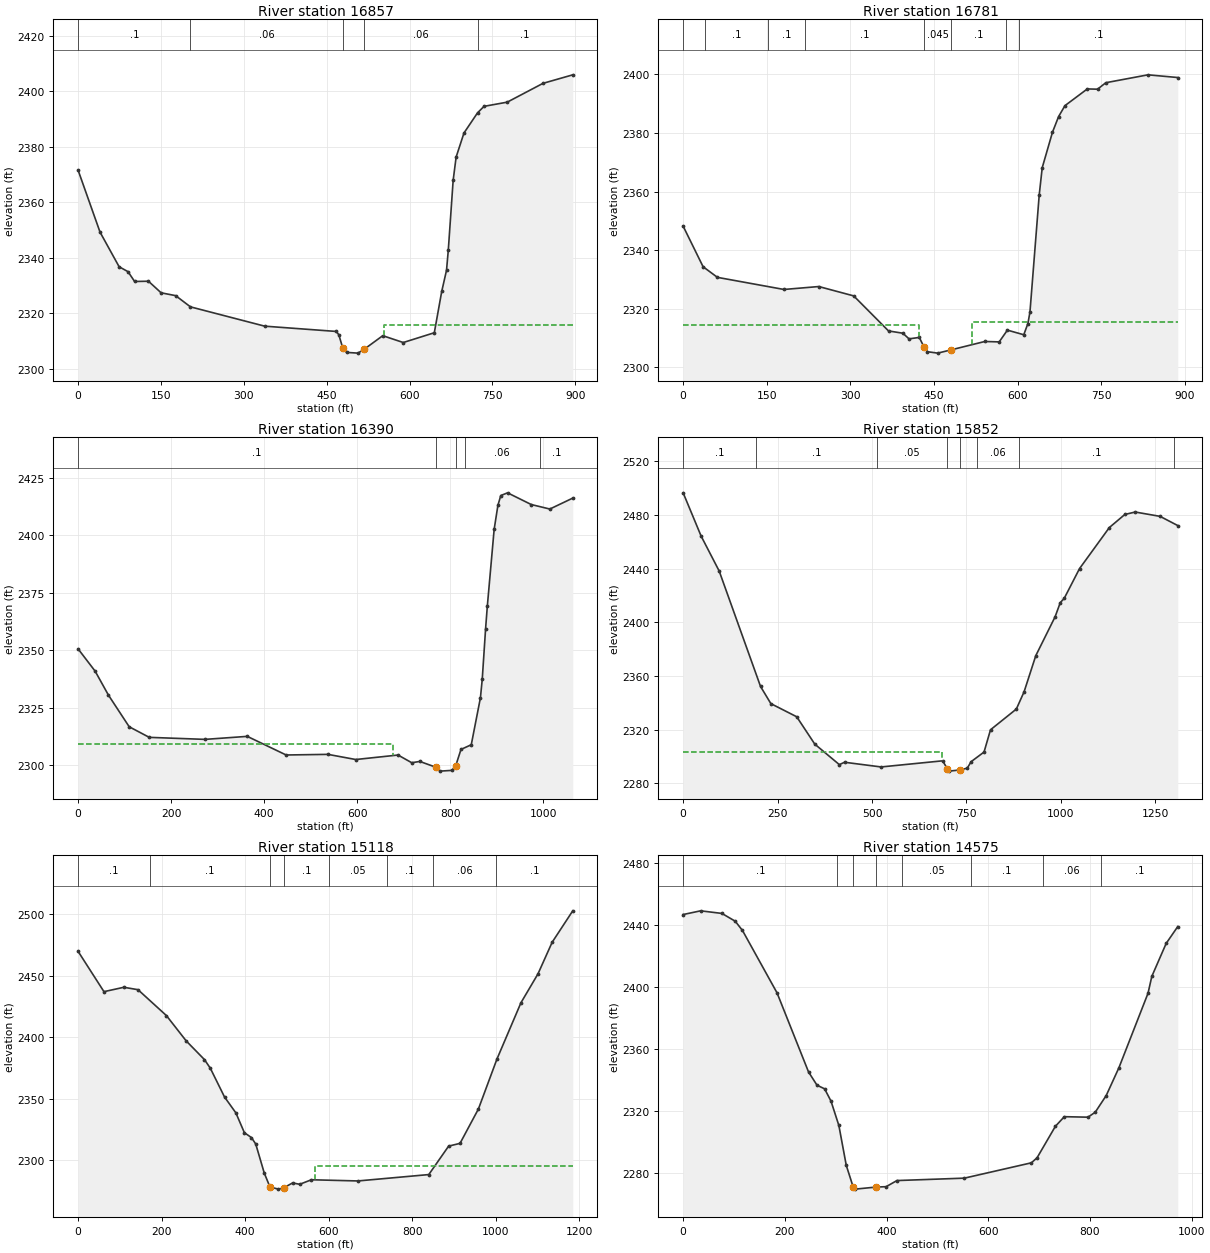
Type RM Length L Ch R = 1 ,16857   ,80.9,76.5,69.6
XS GIS Cut Line= 5
2156037.09884347398821.6560561892155755.46735476398657.687318829
2155662.85538273398576.4620646732155611.23559505 398527.11962056
2155296.96218177398322.917813384
#Sta/Elev= 30
       0 2371.47    39.6 2349.22    74.2 2336.74    90.3 2334.97   102.2 2331.44
   127.3 2331.53   150.2 2327.36   176.5 2326.34   203.3  2322.3   337.7 2315.35
   467.2 2313.45   471.8 2312.27   479.1 2307.41   485.8  2305.9   506.6 2305.64
   518.2  2307.1   551.4 2311.92   588.5 2309.46   644.7 2312.98   658.1 2327.84
   666.8 2335.48     670 2342.69   678.8 2367.84   684.2 2376.25   698.4 2384.92
   722.9 2392.16   734.7 2394.51   776.7 2396.02   841.4 2402.79   895.3 2405.86
#Mann= 5 ,-1 , 0
       0      .1       0   203.3     .06       0   479.1    .045       0
   518.2     .06       0   722.9      .1       0
#XS Ineff= 2 , 0
                          553.48         2315.83
Permanent Ineff=
       F       F
Bank Sta=479.1,518.2
XS Rating Curve= 0 ,0
Exp/Cntr(USF)=0,0
Exp/Cntr=0.5,0.3

Type RM Length L Ch R = 1 ,16781   ,392.4,391,390.2
XS GIS Cut Line= 2
2156068.75306214398681.8939716372155277.08633839398280.852450892
#Sta/Elev= 30
       0 2348.18    35.8 2334.34    61.5 2330.72   180.9 2326.59   243.4 2327.59
     306  2324.4   368.5 2312.45   394.2 2311.67   405.3 2309.75   423.7 2310.23
  432.26 2306.93   438.4 2305.36   456.8 2304.88  481.382306.022   541.3 2308.85
   567.1 2308.71   581.8 2312.72   611.2 2311.15   618.6 2314.97   622.3 2318.89
   638.9 2358.81   644.3 2368.12   662.7 2380.22   673.7 2385.56   685.1 2389.28
   725.2 2394.98   743.6 2394.89   758.4  2397.1   834.1 2399.79   887.5 2398.87
#Mann= 8 ,-1 , 0
       0      .1       0   39.32      .1       0  151.59      .1       0
  218.83      .1       0  432.26    .045       0  481.38      .1       0
  579.87     .06       0  602.62      .1       0
#XS Ineff= 2 ,-1
       0  423.88 2314.47  518.39  887.45 2315.38
Permanent Ineff=
       F       F
Bank Sta=432.26,481.38
XS Rating Curve= 0 ,0
Exp/Cntr=0.3,0.1

Type RM Length L Ch R = 1 ,16390   ,540.7,537.4,537.7
XS GIS Cut Line= 2
 2156507.9890603398449.2553293112155547.91978621397990.921928391
#Sta/Elev= 30
       0 2350.55    36.6 2340.87    65.2 2330.45   109.8  2316.7     153 2312.09
   272.9 2311.21   363.8 2312.52   447.4 2304.42   537.3 2304.69   597.1 2302.45
   688.1  2304.4   717.6 2301.05   734.9 2301.62  769.532299.088   778.3  2297.4
   803.8 2297.72  811.812299.521   823.5 2306.84   845.6 2308.88   865.3  2329.3
   869.2 2337.32   876.4  2359.3   880.1 2369.07   894.8 2402.52   902.9 2413.01
   909.1 2417.28   923.7 2418.46   974.6 2413.37  1014.6 2411.41  1063.9 2416.16
#Mann= 5 ,-1 , 0
       0      .1       0  769.53    .045       0  811.81      .1       0
  831.52     .06       0  992.96      .1       0
#XS Ineff= 2 , 0
          677.08 2309.02
Permanent Ineff=
       F       F
Bank Sta=769.53,811.81
XS Rating Curve= 0 ,0
Exp/Cntr=0.3,0.1

Type RM Length L Ch R = 1 ,15852   ,744.2,734.6,726.3
XS GIS Cut Line= 2
2156855.21146297 397933.63004823 2155599.1680433397563.984462067
#Sta/Elev= 30
       0 2496.42    47.6 2464.16    95.4 2438.13   204.9 2352.09   232.2 2339.32
   300.6 2329.53   348.5 2309.13   413.5 2293.86   427.2 2295.63     524 2292.13
   687.1 2296.71  699.232290.725   704.2 2289.02  733.212289.895   752.1 2291.27
   762.3 2296.07   796.5 2303.24   813.6 2319.83     882 2335.28   902.5 2348.14
   933.5 2375.08   984.6 2404.03   998.3 2414.61  1008.6  2417.7  1049.2 2439.92
  1128.3 2470.58  1169.3 2480.31  1196.7 2482.11  1262.5 2478.88  1309.3 2472.03
#Mann= 8 ,-1 , 0
       0      .1       0  192.74      .1       0  512.98     .05       0
  699.23    .045       0  733.21     .05       0  779.04     .06       0
  889.19      .1       0 1300.07      .1       0
#XS Ineff= 2 , 0
          686.13 2303.08
Permanent Ineff=
       F       F
Bank Sta=699.23,733.21
XS Rating Curve= 0 ,0
Exp/Cntr=0.3,0.1

Type RM Length L Ch R = 1 ,15118   ,544,542.6,541.7
XS GIS Cut Line= 2
2156784.03083105396902.380142227 2155639.9337098397207.935633481
#Sta/Elev= 30
       0 2469.75    61.8 2437.02   109.4 2440.59   143.3 2438.63   211.3 2417.58
   258.8 2396.93   302.5 2381.73   316.4 2374.78   350.5 2351.31   377.6 2338.45
     398 2322.31     415 2318.31   425.2 2313.09   445.6 2289.48  459.252278.122
   479.5  2276.4  492.052277.476   513.5 2281.43   530.5 2280.34   558.5 2284.02
   669.7 2283.05   839.5 2288.24     887 2311.37   914.3 2313.63   958.3 2341.56
  1002.7  2382.2  1060.2 2428.03    1101 2451.54  1134.9 2477.23  1184.2 2502.78
#Mann= 8 ,-1 , 0
       0      .1       0  171.01      .1       0  459.25    .045       0
  492.05      .1       0  601.73     .05       0  739.48      .1       0
  848.67     .06       0 1001.04      .1       0
#XS Ineff= 2 , 0
                          566.43         2294.85
Permanent Ineff=
       F       F
Bank Sta=459.25,492.05
XS Rating Curve= 0 ,0
Exp/Cntr=0.3,0.1

Type RM Length L Ch R = 1 ,14575   ,638.4,637.2,631.7
XS GIS Cut Line= 2
2156362.15569055396426.6858836412155469.79461439396813.838652641
#Sta/Elev= 30
       0 2446.54    34.4 2448.92    76.2 2447.25   102.4 2442.24   116.7 2436.27
   184.6 2396.19   246.6 2345.28   263.2 2336.79   278.2 2334.43   290.7 2326.58
   306.2 2310.89   320.8  2285.2  334.072271.604   338.4 2269.93  379.922271.273
   399.2  2271.5   420.4 2275.44     553 2276.99   684.8 2286.85     696 2290.08
   732.1 2310.36   749.6 2316.52   796.2  2316.2   810.5 2319.44     832 2330.12
     857 2348.02   914.2 2395.89   921.7 2406.77   949.9 2427.96   972.7  2438.8
#Mann= 8 ,-1 , 0
       0      .1       0  303.27      .1       0  334.07    .045       0
  379.92      .1       0  431.16     .05       0  566.98      .1       0
  707.66     .06       0  821.29      .1       0
Bank Sta=334.07,379.92
XS Rating Curve= 0 ,0
Exp/Cntr=0.3,0.1

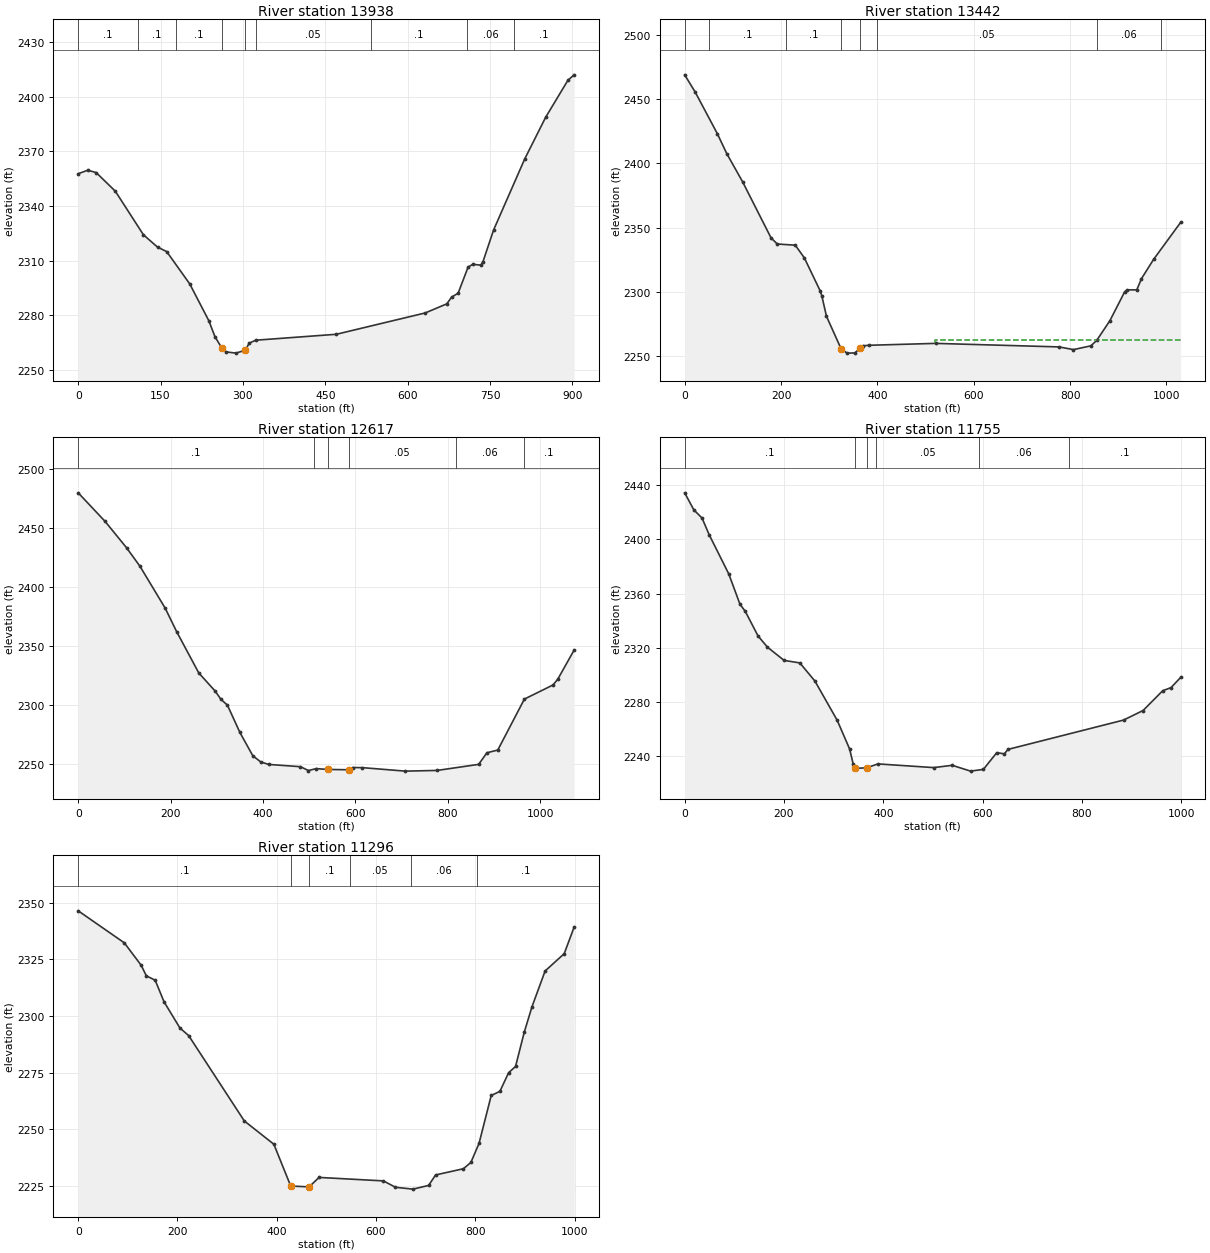
Type RM Length L Ch R = 1 ,13938   ,479.7,496.2,505.5
XS GIS Cut Line= 2
2155876.04478614395933.6301112322155110.41967697396412.796803817
#Sta/Elev= 30
       0 2357.75    17.2 2359.67    32.7  2358.4    67.6 2348.14   118.8 2324.15
   144.4  2317.4   161.1 2314.93     203  2297.2   237.9 2276.88   249.1 2268.05
   261.82261.775   268.8 2259.77   287.2 2259.06  304.34 2260.67   311.4 2264.53
     323 2266.16   470.1 2269.43     632 2281.17   671.3 2286.18     680 2289.86
   691.9 2292.03     710 2306.36   718.6 2307.94   733.3 2307.46   737.2 2309.42
   756.5 2326.83   813.3 2365.97   851.4 2388.87   891.9 2409.19   903.2 2412.17
#Mann= 9 ,-1 , 0
       0      .1       0  109.34      .1       0  178.19      .1       0
   261.8    .045       0  304.34      .1       0  323.23     .05       0
  533.04      .1       0  707.63     .06       0  794.02      .1       0
Bank Sta=261.8,304.34
XS Rating Curve= 0 ,0
Exp/Cntr=0.3,0.1

Type RM Length L Ch R = 1 ,13442   ,824.5,824.8,837.3
XS GIS Cut Line= 2
2155912.50304656395629.8108369712154884.72524647 395572.51895681
#Sta/Elev= 30
       0 2468.81    21.6 2455.56    67.6 2423.17    87.3 2407.57   120.2 2385.62
   179.3 2341.95   192.2 2337.22   229.6 2336.29   248.3 2326.49   281.2  2300.8
   284.5 2297.13   294.3 2281.01  324.552255.773     337 2252.33   353.5  2252.5
  363.892256.152   369.9 2258.03     383 2258.44     521 2259.91   777.4 2257.16
   806.9 2255.06   843.1    2258   855.2  2262.2   882.5 2277.51     913 2299.82
   918.6 2301.56   938.4 2301.51   948.2 2310.29   973.4  2325.3  1029.4    2354
#Mann= 8 ,-1 , 0
       0      .1       0   50.65      .1       0  210.19      .1       0
  324.55    .045       0  363.89      .1       0  399.94     .05       0
  856.19     .06       0   989.4      .1       0
#XS Ineff= 1 ,-1
  518.79 1029.37 2262.51
Permanent Ineff=
       F
Bank Sta=324.55,363.89
XS Rating Curve= 0 ,0
Exp/Cntr=0.3,0.1

Type RM Length L Ch R = 1 ,12617   ,859.3,861.8,863.7
XS GIS Cut Line= 2
2155903.82228963394996.1300177282154879.51692355394674.949557722
#Sta/Elev= 30
       0 2479.46    58.2 2455.29   104.6 2433.05   133.8 2417.29   188.4 2381.85
   212.9 2362.22     261 2327.16   296.6 2311.78   309.2 2304.74   322.9 2300.03
     350 2276.86   377.9 2257.21   395.1 2251.94   412.3 2249.85   481.1 2247.92
   498.3 2244.68   515.3 2246.31  540.012245.603  585.83 2245.33   594.6 2247.21
   615.2 2247.12     708 2244.18   776.8 2244.76   866.8  2249.9   884.7 2259.69
   908.2 2262.01   965.8 2305.08  1027.8 2317.03  1038.1 2321.94  1073.5 2346.57
#Mann= 6 ,-1 , 0
       0      .1       0  509.65     .05       0  540.01    .045       0
  585.83     .05       0   817.1     .06       0  965.33      .1       0
Bank Sta=540.01,585.83
XS Rating Curve= 0 ,0
Exp/Cntr=0.3,0.1

Type RM Length L Ch R = 1 ,11755   ,459.1,459.4,460.6
XS GIS Cut Line= 2
2156103.47510555394256.5468512332155188.54452072393855.505330473
#Sta/Elev= 30
       0  2434.5    18.4 2421.93      35 2415.82    49.3 2403.52    88.8 2374.54
   111.3 2352.18   122.2 2346.76   147.9 2328.58   166.8 2320.35   200.2 2310.59
     232 2308.71   262.5 2295.22   307.3 2266.23   332.3    2245   339.5 2233.85
  342.712230.722  366.832231.156   389.2 2234.03   501.6  2231.3   538.9 2232.99
   575.9 2228.69   601.7 2229.99   628.6 2242.33     644 2241.49   651.2 2244.76
     884 2266.44   923.4 2273.52   962.8  2288.1   979.8 2290.49     999 2297.97
#Mann= 6 ,-1 , 0
       0      .1       0  342.71    .045       0  366.83      .1       0
   384.9     .05       0  593.13     .06       0  773.36      .1       0
Bank Sta=342.71,366.83
XS Rating Curve= 0 ,0
Exp/Cntr=0.3,0.1

Type RM Length L Ch R = 1 ,11296   ,334.5,333.5,330.9
XS GIS Cut Line= 2
2156266.66966106393822.5191759772155330.90578455393471.824667394
#Sta/Elev= 30
       0 2346.38    92.9 2332.27     127 2322.35   137.2 2317.73   155.1 2315.79
   172.9 2306.29     205 2294.71   222.5  2291.4   334.7 2253.75   394.2 2243.49
  428.182225.067  465.262224.693   485.3 2228.86     615 2227.33   639.3 2224.51
   674.5  2223.7   706.1 2225.33   720.1 2229.95   776.1 2232.69   791.2 2235.46
   807.7 2243.89   832.2 2264.98   849.7  2266.8   867.2    2275   881.2 2277.77
   898.8 2292.91   914.5  2304.2   940.8 2319.87   979.3  2327.5   999.3 2339.24
#Mann= 6 ,-1 , 0
       0      .1       0  428.18    .045       0  465.26      .1       0
  547.02     .05       0  669.59     .06       0  803.27      .1       0
Bank Sta=428.18,465.26
XS Rating Curve= 0 ,0
Exp/Cntr=0.3,0.1