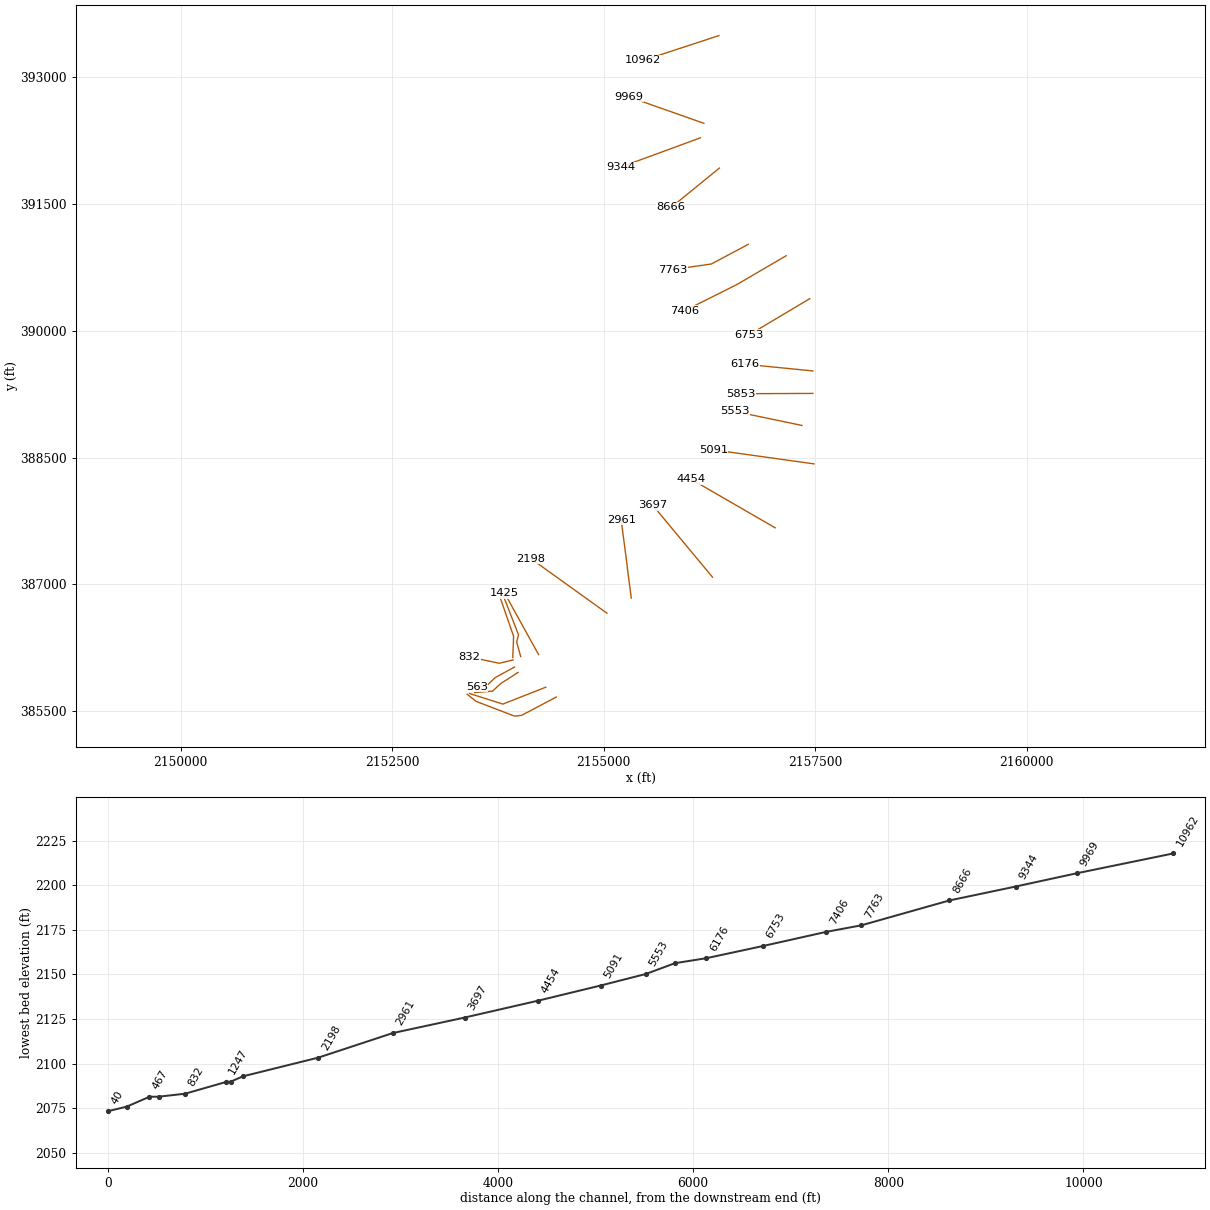
HEC-RAS study ROBBINSRN.prj: ROBBINSRN

--- ROBBINSRN.g01 (geometry) --- (continued)

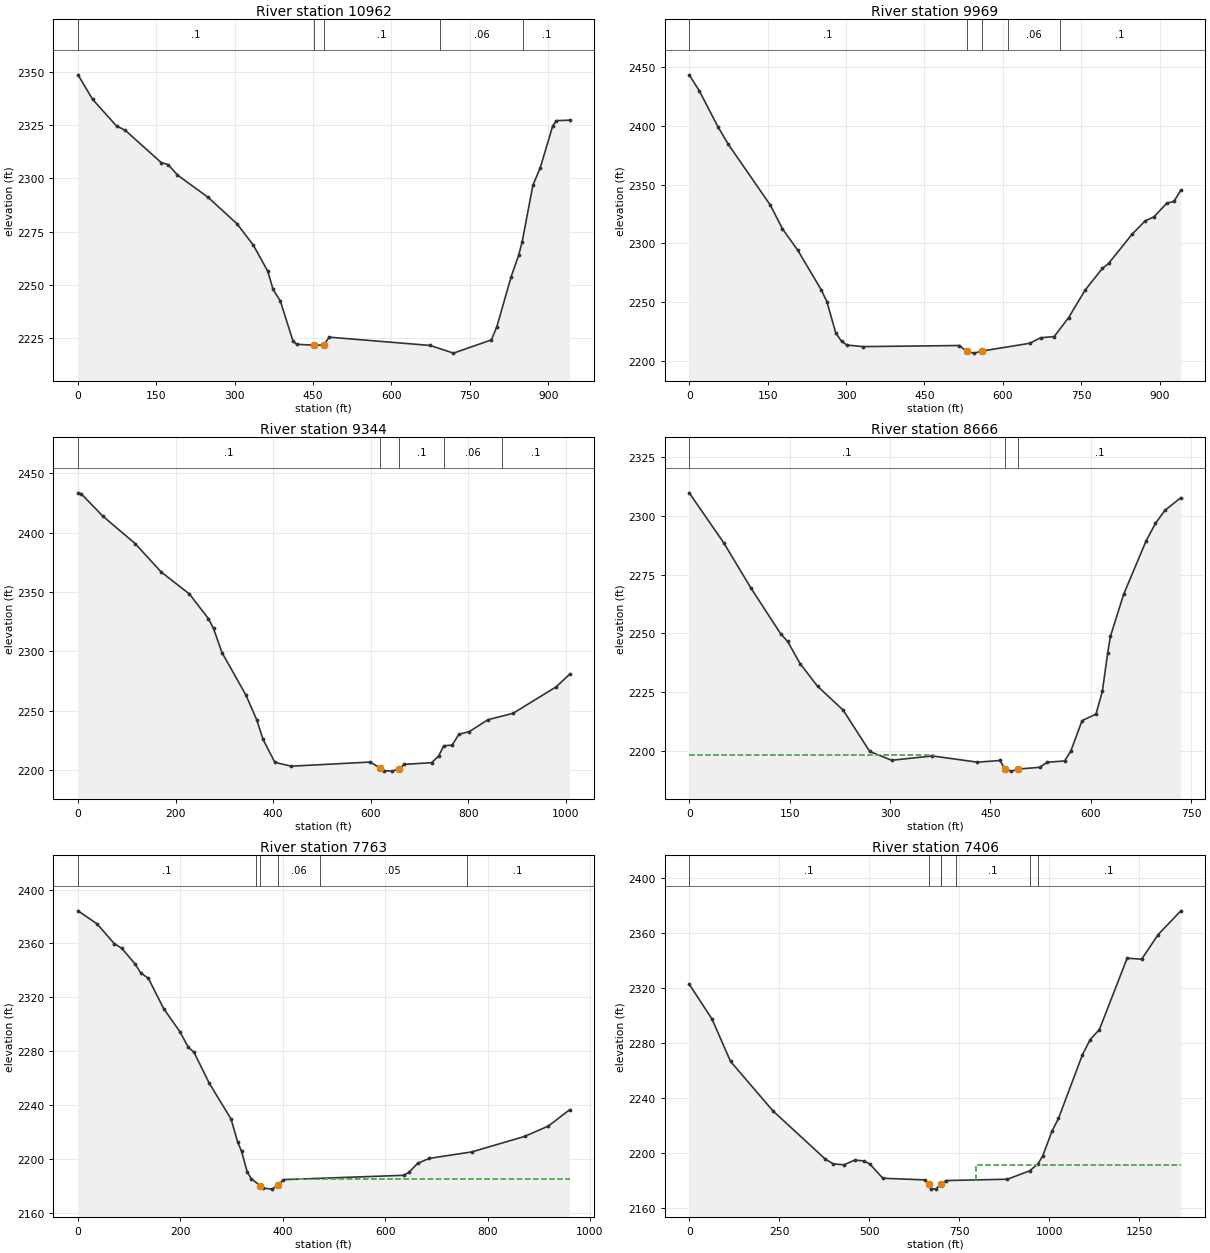
Type RM Length L Ch R = 1 ,10962   ,993.9,993.6,985.1
XS GIS Cut Line= 2
2156363.89190756393487.4496361462155469.79461439393194.047007725
#Sta/Elev= 30
       0 2348.69    28.1 2337.12    73.7 2324.64    90.3 2322.62   159.4  2307.4
   172.5  2306.5   190.4 2301.57   249.1 2291.07   304.4 2278.63   335.5 2268.65
   363.1 2256.39   373.4 2247.81   387.3 2242.31   411.4 2223.59   418.3 2221.98
  452.432221.537  470.752221.608   480.5 2225.32   673.9 2221.43   718.7 2217.81
   791.3 2224.04   801.7 2230.24   829.2 2253.84   843.3 2263.74     850 2269.96
   870.7 2296.75   884.9 2305.09   908.7  2324.7   915.6 2327.14     941 2327.37
#Mann= 5 ,-1 , 0
       0      .1       0  452.43    .045       0  470.75      .1       0
  692.57     .06       0  852.46      .1       0
Bank Sta=452.43,470.75
XS Rating Curve= 0 ,0
Exp/Cntr=0.3,0.1

Type RM Length L Ch R = 1 ,9969    ,611.6,625.1,637.3
XS GIS Cut Line= 2
 2156185.0723833392450.9914072312155297.91963005392763.491438389
#Sta/Elev= 30
       0 2443.35    19.6 2429.49    54.9 2399.23    74.8 2384.26   155.4 2332.43
   178.4 2312.36   207.5  2294.3   252.7 2260.43   263.3 2250.54   280.5 2223.69
   291.6 2216.65   301.9 2213.52   332.6 2212.19   517.1 2213.12  530.92 2208.04
   544.9 2206.65  560.422208.454   651.7 2215.03   672.3 2219.71   698.3 2220.76
   725.8 2236.78   757.5 2260.25   790.6 2278.77   802.3 2282.89   847.2  2307.7
   871.9 2318.92   889.2 2322.63   913.6 2334.11   927.5  2335.8   940.6 2345.19
#Mann= 5 ,-1 , 0
       0      .1       0  530.92    .045       0  560.42      .1       0
  610.75     .06       0  708.59      .1       0
Bank Sta=530.92,560.42
XS Rating Curve= 0 ,0
Exp/Cntr=0.3,0.1

Type RM Length L Ch R = 1 ,9344    ,668.8,677.4,683.5
XS GIS Cut Line= 2
2156145.14201698392279.1164228922155198.96149464 391931.89402023
#Sta/Elev= 30
       0 2433.56     6.1 2432.96    50.6 2414.06     117 2390.89   170.5 2366.92
   228.5 2348.36   267.3 2327.66   277.8 2319.35   295.2 2299.05   344.2 2263.36
   366.6  2242.3   379.3 2226.05   403.6  2206.6   437.1 2203.39   599.3 2206.88
  618.472202.008   627.2  2199.6   644.7 2199.23  657.742201.242   669.2 2204.93
   725.1 2206.36   739.1 2211.82     750  2220.6     767  2221.1     781 2230.31
     802 2232.43   840.4 2242.52     892 2247.92   980.4 2270.24  1007.9 2280.79
#Mann= 5 ,-1 , 0
       0      .1       0  618.47    .045       0  657.74      .1       0
  749.85     .06       0  869.73      .1       0
Bank Sta=618.47,657.74
XS Rating Curve= 0 ,0
Exp/Cntr=0.3,0.1

Type RM Length L Ch R = 1 ,8666    ,903.5,903,899.1
XS GIS Cut Line= 2
2156369.10023047 391921.477374392155799.65583131391457.935650557
#Sta/Elev= 30
       0 2309.77    51.4  2288.6    92.4 2269.19   136.7 2249.81     147 2246.57
   165.7 2237.13   191.7 2227.54     230 2217.36   269.6 2199.82   302.3 2196.07
   363.2 2197.91   430.4 2195.26   464.2 2195.97  471.582192.298   481.2 2191.45
  491.742192.331   523.5 2193.07   534.7 2195.24   560.7 2195.78     570 2199.99
   586.8 2212.93   607.5 2215.65   617.1 2225.41     625 2241.59   629.2 2248.85
     649 2266.72   682.4 2289.31   696.4 2296.78   710.4 2302.29   734.3 2307.71
#Mann= 3 ,-1 , 0
       0      .1       0  471.58    .045       0  491.74      .1       0
#XS Ineff= 2 , 0
          364.91 2198.12
Permanent Ineff=
       F       F
Bank Sta=471.58,491.74
XS Rating Curve= 0 ,0
Exp/Cntr=0.3,0.1

Type RM Length L Ch R = 1 ,7763    ,356.8,357.2,357.2
XS GIS Cut Line= 3
2156711.11398214391020.4358693962156273.61420096390787.796898976
2155813.54458305390721.824589983
#Sta/Elev= 30
       0 2384.27    37.1 2374.64    70.9 2359.88    85.5 2356.48   112.2 2344.47
   122.6 2338.09   137.4 2334.16   167.2  2311.7   199.5 2294.21   215.5 2282.89
   226.6 2279.19   256.3 2256.27     299 2229.55   312.1 2212.24   319.5 2205.65
   330.5 2190.32   338.1 2185.39  355.332180.139   360.4 2178.31     379  2177.5
  391.192180.505   401.3 2184.56   636.8 2187.78   646.8 2190.07   663.3 2196.66
   686.5 2200.37   769.4 2205.17   872.3 2216.65   918.7 2224.35   960.3 2236.47
#Mann= 6 ,-1 , 0
       0      .1       0   347.6     .06       0  355.33    .045       0
  391.19     .06       0  472.33     .05       0  759.41      .1       0
#XS Ineff= 1 ,-1
  413.89  960.28 2184.89
Permanent Ineff=
       F
Bank Sta=355.33,391.19
XS Rating Curve= 0 ,0
Exp/Cntr=0.3,0.1

Type RM Length L Ch R = 1 ,7406    ,651.4,652.8,653.6
XS GIS Cut Line= 5
2157158.15278623390885.5198006482156586.47840464 390551.37315923
2156568.88624822390541.8593987232156551.29409181390532.345310137
2155957.62926863390235.027335227
#Sta/Elev= 30
       0 2322.88    63.3  2297.5   114.9  2266.7   232.7 2230.72   377.1 2195.96
   399.9 2192.24   430.2 2191.55   460.7 2195.06   485.4 2194.34   501.5 2192.23
   538.1 2181.78   654.6 2180.57  665.022177.338   672.5  2174.1   684.5 2173.87
  699.312177.277   713.8 2180.11   884.4 2181.07   946.1 2187.19   969.5 2192.32
   982.7 2198.21  1007.7 2215.78  1026.1 2225.23  1092.7 2271.58  1114.1 2282.51
  1139.8 2289.87  1216.9 2341.73  1257.2 2340.99    1303 2358.87  1366.1 2376.15
#Mann= 7 ,-1 , 0
       0      .1       0  665.02    .045       0  699.31      .1       0
  700.36     .06       0  742.69      .1       0  945.88     .05       0
  967.87      .1       0
#XS Ineff= 2 , 0
                          797.06         2191.14
Permanent Ineff=
       F       F
Bank Sta=665.02,699.31
XS Rating Curve= 0 ,0
Exp/Cntr=0.3,0.1

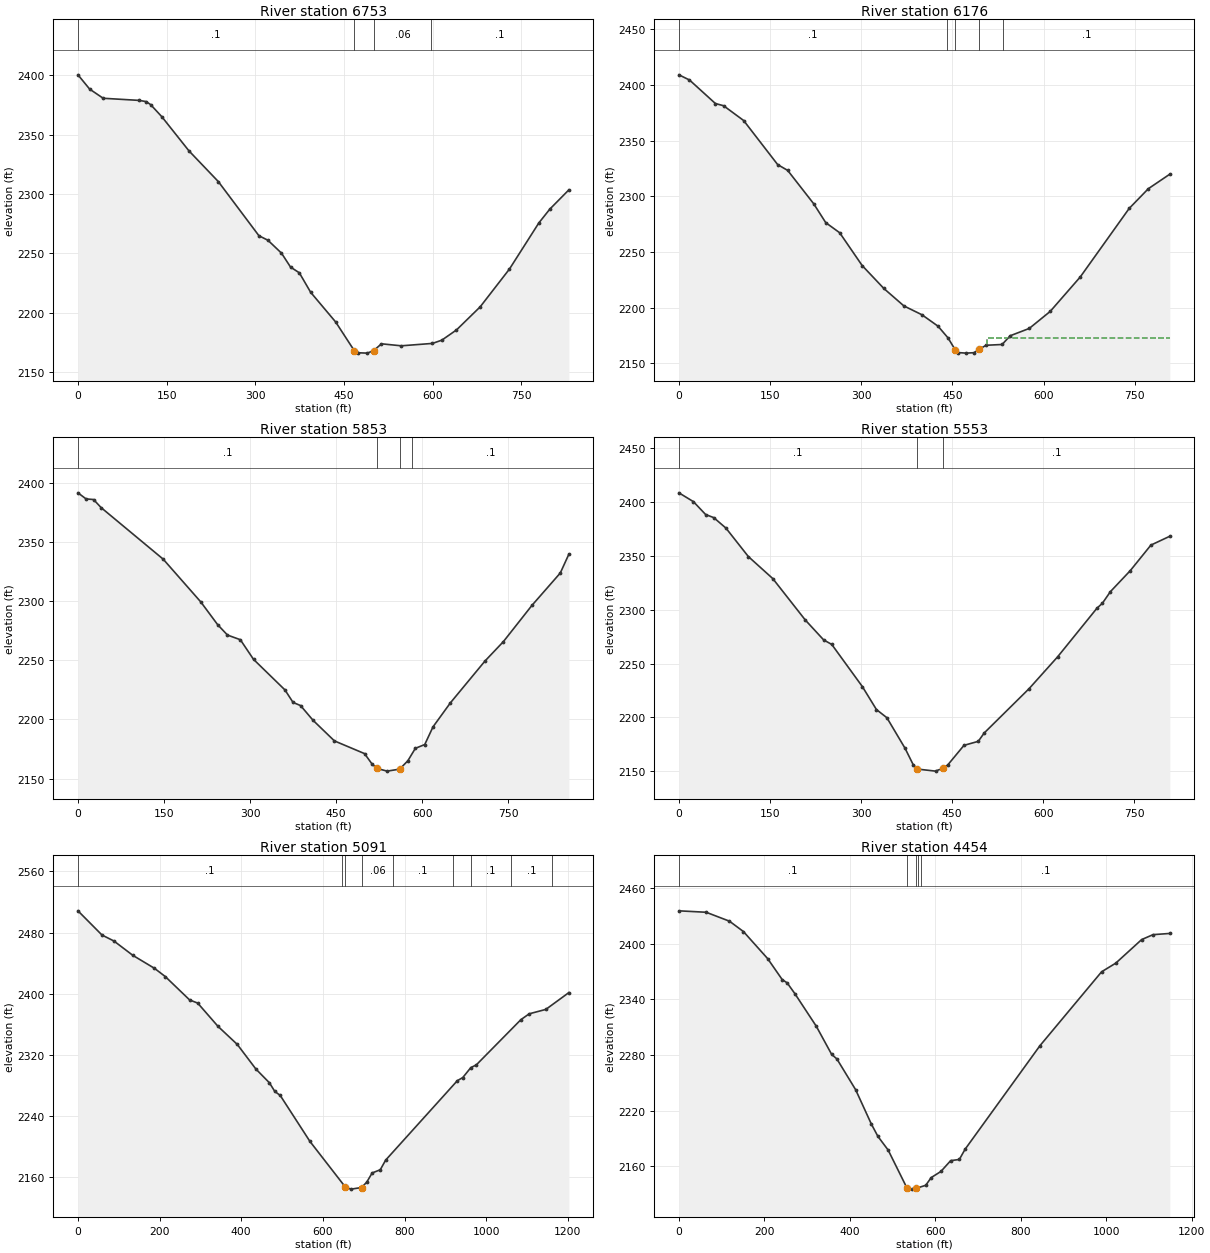
Type RM Length L Ch R = 1 ,6753    ,588.6,577.3,567.8
XS GIS Cut Line= 2
2157436.80839689390378.0746213052156723.26684497389952.727374896
#Sta/Elev= 30
       0 2400.56    19.8 2388.51    42.7 2380.79   103.8 2378.99   115.3    2378
   122.9 2375.47     142 2365.18   187.8 2336.45   237.5 2310.54   306.2 2264.88
   321.5 2261.05   344.4 2250.19   359.7 2238.45   374.6 2233.59   393.8 2217.15
   436.1 2192.11  467.682167.885   474.3 2166.17   489.7 2165.88  500.382168.024
   513.6 2173.74   547.1 2172.05   599.8 2174.07   615.6 2176.79   640.5 2185.43
   680.6 2204.92   730.2 2236.84   779.9  2275.7   798.4  2287.3   830.7 2303.58
#Mann= 4 ,-1 , 0
       0      .1       0  467.68    .045       0  500.38     .06       0
  597.96      .1       0
#XS Ineff= 2 , 0
                          515.88         2173.37
Permanent Ineff=
       F       F
Bank Sta=467.68,500.38
XS Rating Curve= 0 ,0
Exp/Cntr=0.3,0.1

Type RM Length L Ch R = 1 ,6176    ,321.6,323.5,325.7
XS GIS Cut Line= 2
2157473.26698539389523.908022568 2156669.4473988389603.769083306
#Sta/Elev= 30
       0 2409.14    17.4 2404.49      60 2383.37    73.5 2381.37   106.5 2368.09
   162.5 2328.48     179 2323.25   221.9 2293.21   241.6 2276.32   264.5 2267.26
   301.6 2237.73   337.2 2217.18   370.2  2201.5   399.9 2193.56   426.3 2183.32
   442.8 2172.78  454.582162.094   459.2  2159.6   472.4 2159.09   485.6 2159.48
  493.822162.452   505.4 2166.15   531.8 2166.85     545 2174.68   576.4 2181.25
   610.9 2196.55   660.4 2227.53   740.9 2289.11   772.4 2306.82   807.8 2319.89
#Mann= 5 ,-1 , 0
       0      .1       0  440.62     .06       0  454.58    .045       0
  493.82     .06       0  533.11      .1       0
#XS Ineff= 1 ,-1
  506.51  807.78 2172.24
Permanent Ineff=
       F
Bank Sta=454.58,493.82
XS Rating Curve= 0 ,0
Exp/Cntr=0.3,0.1

Type RM Length L Ch R = 1 ,5853    ,301.9,299.3,292.7
XS GIS Cut Line= 2
2157473.26698539389258.2828976362156617.36416964389254.810791731
#Sta/Elev= 30
       0 2391.79    14.1 2386.65    27.2 2386.11    40.3 2379.31   148.6 2335.65
   214.2 2299.42   243.7 2280.11   260.7 2271.42   283.1 2267.48   306.1 2250.86
   360.9 2224.98     375  2214.4   388.1 2211.75   409.9 2199.26   447.1 2181.85
   499.6  2171.1   512.8 2162.23  521.422158.544     539 2156.27  560.772157.948
   575.1 2165.01   588.2 2175.56   604.6 2178.77     619 2193.74   649.4 2214.11
   709.6 2249.44   741.7 2265.87   791.6  2296.6   840.9 2323.94   855.9  2339.9
#Mann= 4 ,-1 , 0
       0      .1       0  521.42    .045       0  560.77     .06       0
  582.67      .1       0
Bank Sta=521.42,560.77
XS Rating Curve= 0 ,0
Exp/Cntr=0.3,0.1

Type RM Length L Ch R = 1 ,5553    ,460.5,462.2,462.9
XS GIS Cut Line= 2
2157344.79480138388879.8108855632156553.12807764389044.741329983
#Sta/Elev= 30
       0 2408.63    23.9 2400.44      44 2388.48    57.4  2385.6    77.5 2375.85
   114.4 2349.43   154.6 2329.01   208.2 2290.51   238.4 2272.06   251.8 2267.83
   302.1 2228.76   325.4 2207.37   342.6 2199.78   372.6 2171.32   385.8 2156.31
  392.872152.103   422.7  2150.2  435.432153.065   442.8 2155.91   469.6 2174.15
   493.1 2177.85   502.9 2185.63   576.9 2226.82   623.8 2256.32   688.8  2301.6
   697.5 2306.02   710.8 2316.88   743.4  2336.3   777.5 2360.09   808.7 2368.33
#Mann= 3 ,-1 , 0
       0      .1       0  392.87    .045       0  435.43      .1       0
Bank Sta=392.87,435.43
XS Rating Curve= 0 ,0
Exp/Cntr=0.3,0.1

Type RM Length L Ch R = 1 ,5091    ,643.8,637.1,631
XS GIS Cut Line= 2
2157487.32076305388425.5903373062156296.18370964388591.616251975
#Sta/Elev= 30
       0 2508.41    58.8 2476.73    88.2 2468.84   134.4 2450.09   187.4 2433.09
   213.9 2422.29   273.5 2391.67   293.4  2387.5   343.1 2357.02   390.3 2333.36
   435.8 2301.18     469 2283.11   482.2  2271.8   495.5 2266.52   568.3 2206.28
   655.42146.252   669.4 2143.76  694.72 2145.87   707.5 2152.92   720.7 2164.95
   740.6 2169.14   753.8 2181.78   929.4 2285.85   942.7 2289.94   962.5 2303.01
   975.8 2306.49  1085.1 2365.81  1105.5 2373.48  1146.2 2379.24  1202.7  2401.3
#Mann= 9 ,-1 , 0
       0      .1       0  646.63     .06       0   655.4    .045       0
  694.72     .06       0  772.64      .1       0  918.38      .1       0
  962.17      .1       0 1061.52      .1       0 1160.87      .1       0
Bank Sta=655.4,694.72
XS Rating Curve= 0 ,0
Exp/Cntr=0.3,0.1

Type RM Length L Ch R = 1 ,4454    ,760.4,756.9,753
XS GIS Cut Line= 2
2157028.82233623387669.7411272232156034.03069064388244.394177392
#Sta/Elev= 30
       0 2435.31    63.7 2433.77   118.3 2424.14     151 2412.95   207.7 2383.77
   241.8 2361.12   253.2 2357.71   271.1 2346.19   321.4 2310.95   357.5 2280.49
   369.5 2275.76   413.5 2242.51   450.2 2205.56   465.6  2192.2   489.6 2177.44
  533.242136.875   544.8 2135.31  554.652136.114   577.5 2139.42   590.4 2147.77
   613.1 2154.37   635.9    2166   656.2 2167.29   669.7 2178.34     845 2290.03
   989.1 2369.59  1022.3 2378.93  1082.8 2404.31  1109.5 2409.63  1148.8 2410.93
#Mann= 5 ,-1 , 0
       0      .1       0  533.24    .045       0  554.65      .1       0
  559.71     .06       0  566.58      .1       0
Bank Sta=533.24,554.65
XS Rating Curve= 0 ,0
Exp/Cntr=0.3,0.1

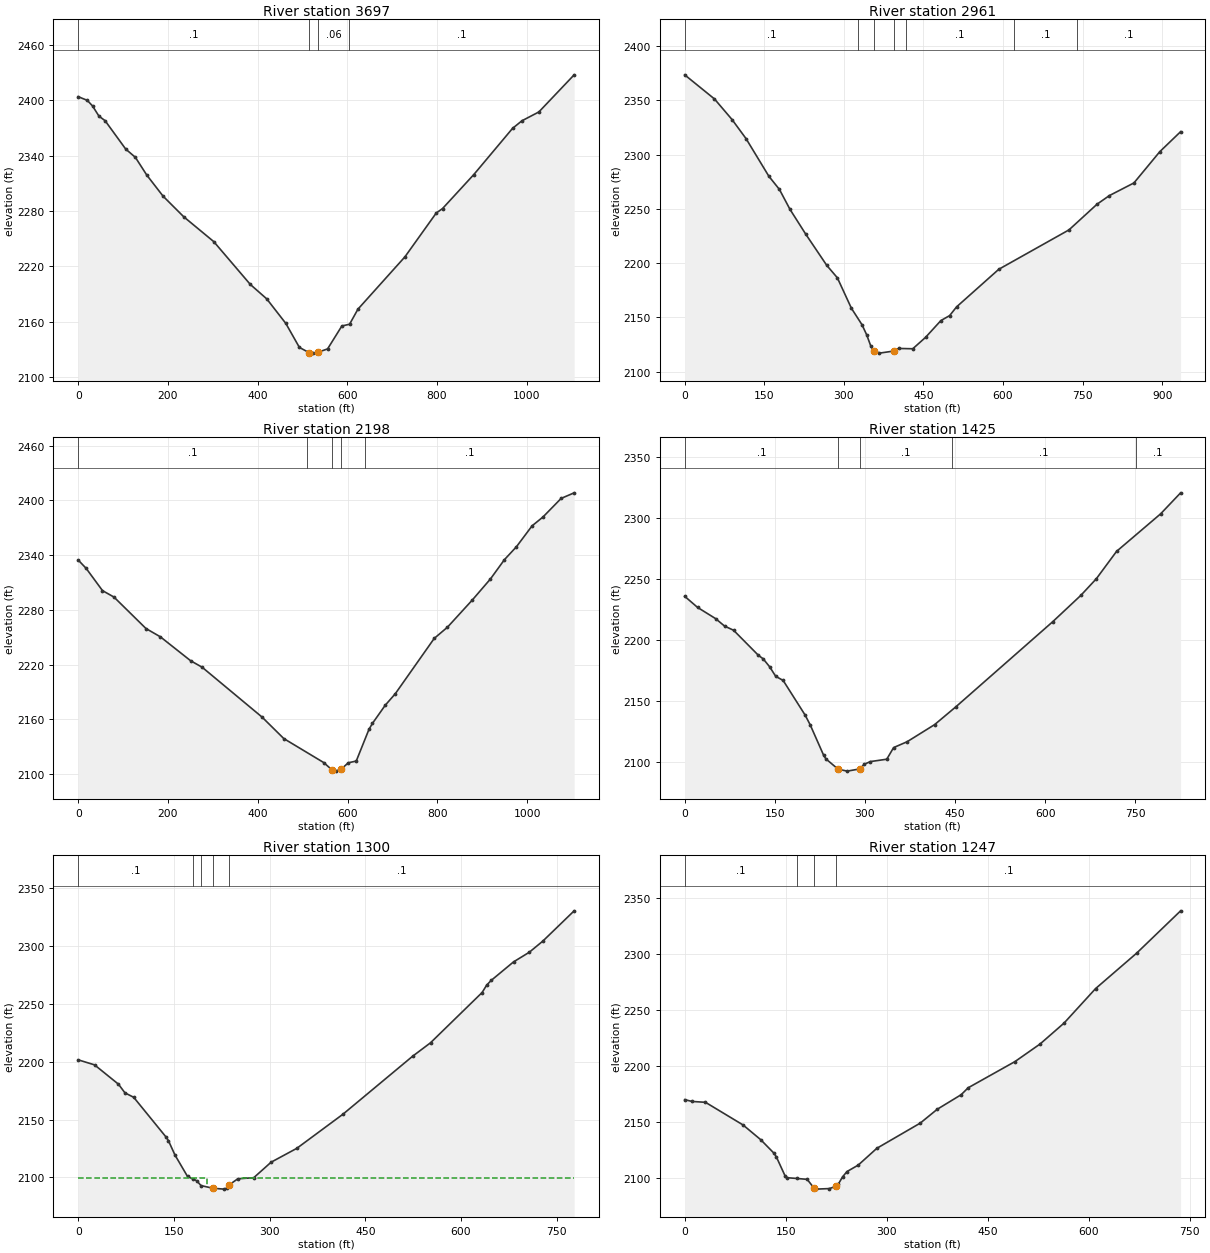
Type RM Length L Ch R = 1 ,3697    ,744,735.7,726.9
XS GIS Cut Line= 2
2156287.50295272387086.4079763142155580.90594073387937.102469146
#Sta/Elev= 30
       0 2404.08    20.3 2400.03    31.9 2394.04    46.2 2382.98    59.9 2378.03
   105.9 2347.22   127.5 2338.23   152.9 2318.99   189.3 2296.08   235.5 2273.66
   302.3 2246.78   383.7 2200.37   420.4 2184.68     463 2158.01   493.2 2132.01
  515.682126.125   523.9 2125.81   535.72126.904   556.1 2130.41   587.9 2155.26
   605.1 2157.15   623.7 2173.47   728.5 2230.26   798.4 2277.85   812.4 2282.66
   882.2 2319.59   968.5 2369.66   989.5 2377.92  1027.2 2387.48  1105.9 2427.77
#Mann= 4 ,-1 , 0
       0      .1       0  515.68    .045       0   535.7     .06       0
  602.99      .1       0
Bank Sta=515.68,535.7
XS Rating Curve= 0 ,0
Exp/Cntr=0.3,0.1

Type RM Length L Ch R = 1 ,2961    ,753,763.3,772.8
XS GIS Cut Line= 5
2155327.43367864386839.8802541492155282.45837489387184.374643892
2155280.54532097387204.2830686422155278.63193896387224.191165313
2155207.64192347387766.963373721
#Sta/Elev= 30
       0 2373.59    56.2 2351.33    89.3 2332.36   115.7 2314.77   158.7 2280.11
   178.6 2267.96   198.5 2249.61   228.2 2226.75   267.9 2197.94   287.8 2186.54
   314.3 2158.44   334.3 2143.25   343.1 2133.94   350.7 2123.79  355.992119.517
   367.1 2117.12  393.972119.027   403.4 2121.43   429.9 2121.14     454 2131.63
   482.9 2147.11   499.4 2151.69   512.6 2159.79     592 2194.37   724.4  2230.7
   777.3 2254.37   800.5  2262.3   846.8 2273.96   895.5 2302.74   934.8  2321.2
#Mann= 7 ,-1 , 0
       0      .1       0  327.33     .06       0  355.99    .045       0
  393.97     .06       0  416.71      .1       0  620.18      .1       0
  739.18      .1       0
Bank Sta=355.99,393.97
XS Rating Curve= 0 ,0
Exp/Cntr=0.3,0.1

Type RM Length L Ch R = 1 ,2198    ,780.5,773.3,765.1
XS GIS Cut Line= 2
2155039.23904505386661.0607298912154141.66964597387305.157866895
#Sta/Elev= 30
       0  2334.7    17.8  2325.5    54.1 2301.17    79.7  2294.1     151 2259.62
   183.1 2250.52   250.3 2224.38   276.2 2217.17   409.5  2162.6   457.9 2139.07
   546.8 2112.77  566.212104.372   573.4 2103.36  586.222105.673   601.6 2112.49
   619.4 2114.41   647.7 2149.13   655.5 2155.69     684 2175.59   706.2 2188.07
   793.1 2248.81   822.6  2261.1   877.9 2290.86   918.3 2313.94   949.5 2335.11
   976.3 2349.28  1011.1 2372.18  1035.4 2381.89  1075.8 2402.23  1104.8 2408.35
#Mann= 5 ,-1 , 0
       0      .1       0  509.67     .06       0  566.21    .045       0
  586.22     .06       0  639.23      .1       0
Bank Sta=566.21,586.22
XS Rating Curve= 0 ,0
Exp/Cntr=0.3,0.1

Type RM Length L Ch R = 1 ,1425    ,134,124.4,114.3
XS GIS Cut Line= 2
2154231.94735256386171.4773914812153832.64204881386893.699700311
#Sta/Elev= 30
       0 2235.97    21.4 2226.89    51.4 2217.72    66.4 2211.59    81.4 2208.17
   122.6  2187.7   130.5 2184.84   141.4 2178.28   151.4 2170.51   163.9 2167.07
   200.5 2138.68   208.9 2130.73   231.4 2105.67   235.1 2102.84  255.442094.422
   270.5 2092.86  291.462094.674   298.8 2098.48   309.1 2100.68   336.3 2102.61
   347.7 2112.14   370.1  2116.9   415.9 2130.92   451.6 2145.64   612.5 2215.18
   659.2  2236.7     685 2250.31   718.7 2272.74     792 2303.46   825.3 2320.67
#Mann= 5 ,-1 , 0
       0      .1       0  255.44    .045       0  291.46      .1       0
  445.15      .1       0  750.81      .1       0
Bank Sta=255.44,291.46
XS Rating Curve= 0 ,0
Exp/Cntr=0.5,0.3

Type RM Length L Ch R = 1 ,1300    ,52.9,53.2,55.1
XS GIS Cut Line= 4
2154020.48612792 386149.123815052153972.87253113386318.945643616
2153995.09220963386404.6501178462153809.39918213386882.373205681
#Sta/Elev= 30
       0 2201.51    25.6 2197.18    63.1 2180.48    73.3 2172.99      87 2169.17
   138.1 2134.59   141.5 2131.67   151.7 2119.32   171.4 2100.81   180.1 2098.59
   185.7 2097.14   192.5 2092.96   211.3 2090.64   228.6 2089.89   233.2 2090.71
   237.12093.734   250.1 2098.78   275.2 2099.76   302.4 2113.13   342.7 2125.11
     415 2154.55   524.1 2204.56   552.3 2216.23   633.2 2259.64   640.3 2265.98
   647.3 2270.03   682.5 2286.09   707.2 2294.42   728.5 2304.08   777.5 2330.17
#Mann= 5 ,-1 , 0
       0      .1       0   180.1     .06       0   192.5      .1       0
   211.3    .045       0   237.1      .1       0
#XS Ineff= 2 , 0
           201.3  2099.3   257.1          2099.3
Permanent Ineff=
       F       F
Bank Sta=211.3,237.1
XS Rating Curve= 0 ,0
Exp/Cntr(USF)=0,0
Exp/Cntr=0.5,0.3

Type RM Length L Ch R = 1 ,1247    ,397.8,415.4,435.9
XS GIS Cut Line= 4
2153926.84605422386136.4268559052153934.78165369386323.707003296
2153936.36877358386388.7789189142153777.65678427386845.869448139
#Sta/Elev= 30
       0 2169.75    11.2 2168.15    30.9 2167.38    86.7 2147.09   112.9 2133.91
   132.7 2121.74   136.3 2118.28   149.1 2101.48   152.4 2099.84   167.1 2099.16
   181.9 2098.38   191.8 2090.78     195 2089.63   214.7 2090.12   224.7 2092.07
   227.9 2093.88   234.4 2100.58     241 2105.36   257.7 2111.15   285.3 2126.18
   349.8 2148.76     375 2161.15   410.5 2174.18   420.9 2180.38   490.4 2203.85
   527.7  2219.6   563.3 2238.33   610.1 2269.21     671 2300.91   736.4 2338.88
#Mann= 4 ,-1 , 0
       0      .1       0   167.1     .06       0   191.8    .045       0
   224.7      .1       0
Bank Sta=191.8,224.7
XS Rating Curve= 0 ,0
Exp/Cntr(USF)=0,0
Exp/Cntr=0.5,0.3

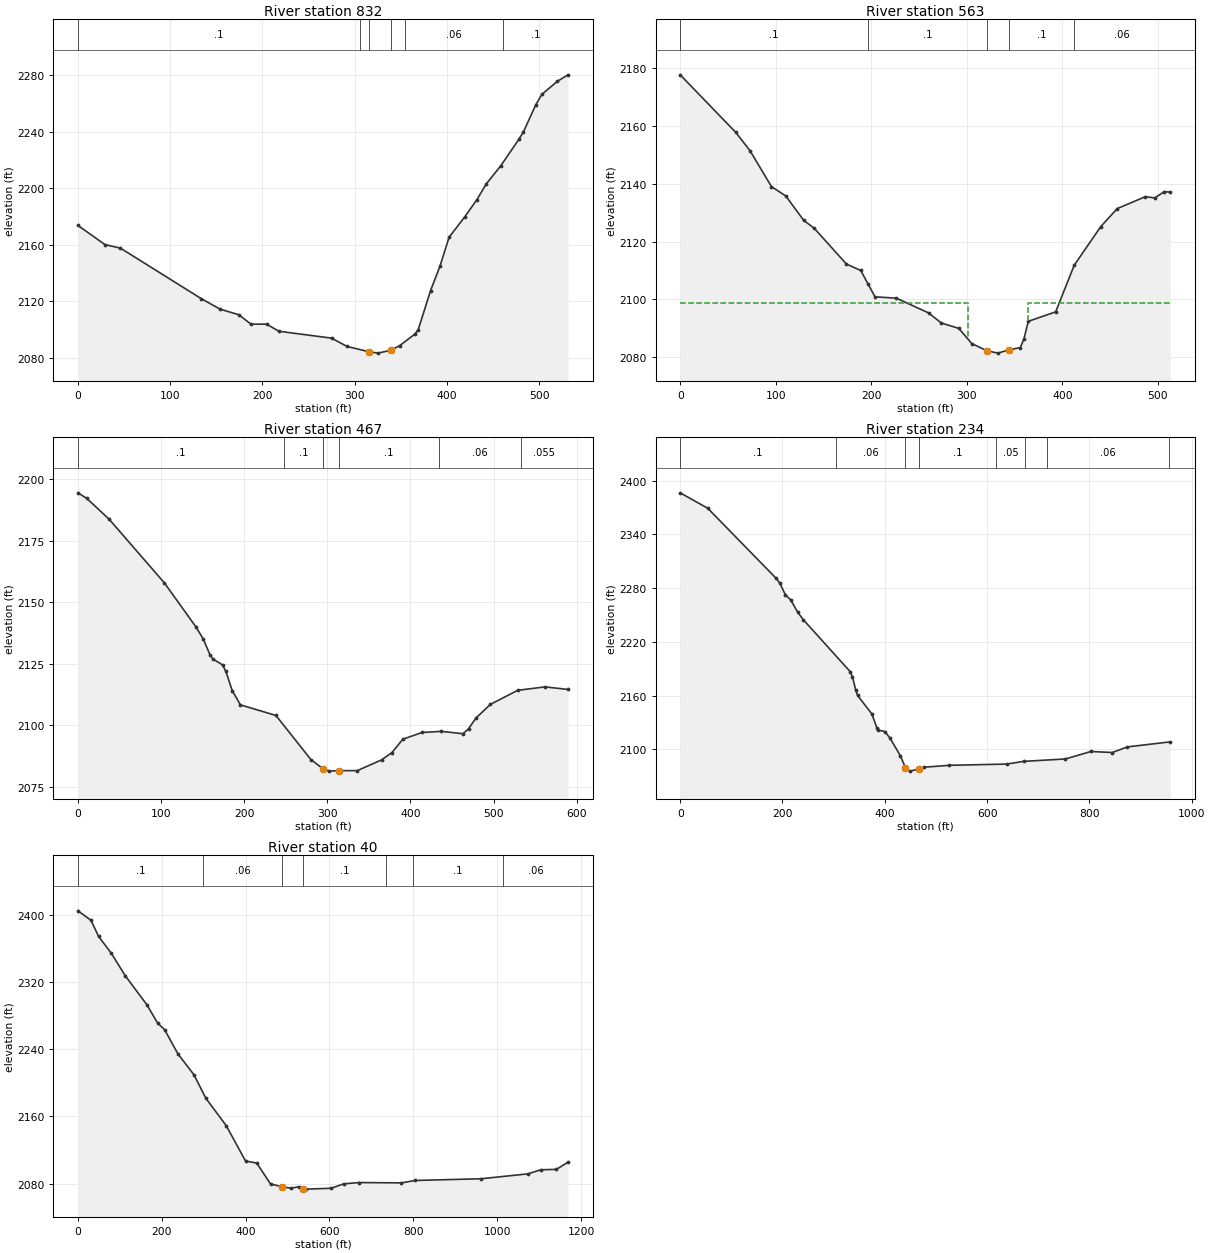
Type RM Length L Ch R = 1 ,832     ,257.8,268.9,280.6
XS GIS Cut Line= 3
2153931.23039648386108.089728821 2153766.6697398386069.046822056
2153412.50312531386143.699559897
#Sta/Elev= 30
       0 2173.59    29.3 2160.01    46.1 2157.49   133.8 2121.66     154 2114.29
   174.2 2110.34   187.6 2103.63   204.4 2103.65   217.8 2098.61   274.8 2093.74
   291.6 2087.86     315 2084.16   325.1 2083.12   339.3 2085.17   348.6 2088.41
   365.3 2096.67   368.7 2099.64   382.1 2127.36   392.2  2144.5   402.2 2165.23
     419 2179.51   432.4 2191.87   442.4 2202.92   458.4 2216.01   477.8 2234.61
   482.7 2239.76   496.1 2258.96   502.8 2266.47   519.3 2275.58   531.1 2280.27
#Mann= 6 ,-1 , 0
       0      .1       0  305.83      .1       0     315    .045       0
   339.3      .1       0   353.9     .06       0  460.59      .1       0
Bank Sta=315,339.3
XS Rating Curve= 0 ,0
Exp/Cntr=0.5,0.3

Type RM Length L Ch R = 1 ,563     ,96,95.7,96.1
XS GIS Cut Line= 5
2153947.30232846386023.8236054652153718.05861655385898.908054724
2153629.51679888385813.8386710582153549.65573813385794.741268307
2153502.78083189385791.269162387
#Sta/Elev= 30
       0  2177.6    58.2 2157.71    73.1 2151.38    95.5 2138.99   110.5 2135.75
   129.2 2127.37   140.4 2124.56     174 2112.23     189 2110.02   196.4 2105.47
   203.9 2100.92   226.3 2100.45   259.9 2095.37   273.4 2091.86   291.6 2090.02
   305.2 2084.77   321.2 2082.28   332.5 2081.47   344.4 2082.63     356 2083.37
   359.8  2086.4   364.3 2092.45     393 2095.72   412.4 2111.83   440.2 2125.18
   457.3 2131.37   486.9 2135.52   496.8 2135.07   506.7 2137.27     513 2137.06
#Mann= 5 ,-1 , 0
       0      .1       0   196.4      .1       0   321.2    .045       0
   344.4      .1       0   412.4     .06       0
#XS Ineff= 2 , 0
           301.2  2098.9   364.4          2098.9
Permanent Ineff=
       F       F
Bank Sta=321.2,344.4
XS Rating Curve= 0 ,0
Exp/Cntr=0.5,0.3

Type RM Length L Ch R = 1 ,467     ,238.4,233.6,228.9
XS GIS Cut Line= 4
2153990.35529864385960.9284031772153787.50303148385831.199528724
2153686.80867906385739.185605139 2153475.0030003385723.560636386
#Sta/Elev= 30
       0 2194.45    10.5 2192.23    37.5 2183.75     104 2157.87   142.1 2139.93
   150.7 2135.12     159 2128.56   162.4 2126.95   174.1 2124.53     178  2121.9
   185.7 2114.05   195.5 2108.32   238.2 2104.02   280.2 2086.13   295.2 2082.26
   302.2 2081.41   313.8 2081.61     336 2081.61   365.2 2085.96   377.8 2088.97
   390.9 2094.38     414  2097.1     437 2097.56   463.3  2096.6   469.9 2098.64
   478.9 2102.99   496.2 2108.52   529.1 2114.24     562 2115.63   589.6 2114.58
#Mann= 6 ,-1 , 0
       0      .1       0  247.95      .1       0   295.2    .045       0
   313.8      .1       0  434.54     .06       0  532.65    .055       0
Bank Sta=295.2,313.8
XS Rating Curve= 0 ,0
Exp/Cntr=0.5,0.3

Type RM Length L Ch R = 1 ,234     ,201.4,193.4,186.1
XS GIS Cut Line= 3
2154317.01673622385786.0608394742153810.07254013385586.408023566
2153415.97523122385711.408101648
#Sta/Elev= 30
       0 2386.36    53.8 2369.16   187.8 2290.85   194.9 2285.44   205.4 2272.87
     216  2266.9   230.1 2252.87   240.5 2244.93   332.4 2186.83   336.7  2181.3
     343 2166.84   346.8 2160.27   374.6 2139.78   384.7 2123.98   387.2  2121.7
   399.9 2120.07     410 2112.86   430.3 2093.18  440.44 2079.78   448.7 2075.86
  467.032078.223   476.9 2080.23   526.3 2082.35   638.4 2083.73   671.3 2086.73
   753.3 2089.45     803 2097.76   844.8 2096.64   874.4 2102.88   958.3 2108.54
#Mann= 8 ,-1 , 0
       0      .1       0  304.87     .06       0  440.44    .045       0
  467.03      .1       0     617     .05       0  674.22      .1       0
   717.4     .06       0  954.81      .1       0
Bank Sta=440.44,467.03
XS Rating Curve= 0 ,0
Exp/Cntr=0.3,0.1

Type RM Length L Ch R = 1 ,40      ,,,
XS GIS Cut Line= 5
2154441.63315246385670.0043654922154032.90878922385453.972685495
2153948.02164715385444.1264002532153493.11824802385618.951155338
2153388.32481665385702.248498221
#Sta/Elev= 30
       0 2405.33    31.2 2394.09    49.2 2374.85    79.3 2354.97   113.3 2327.58
   164.6 2293.18   190.2 2271.29   206.7 2263.65   238.4 2234.77   276.9 2209.64
   305.1 2181.75   353.7  2149.1   399.8 2106.84   426.5 2104.39   459.4 2079.49
   486.22076.258   507.4 2074.41   527.3 2076.09   536.42073.814   543.8 2073.31
   604.1 2074.34   633.8 2079.59     670 2081.15   771.7 2080.78   804.7 2083.64
     961 2085.66  1072.7 2091.49  1104.3 2096.41  1141.2 2096.87    1169 2105.48
#Mann= 7 ,-1 , 0
       0      .1       0   299.4     .06       0   486.2    .045       0
   536.4      .1       0   735.2     .05       0   798.5      .1       0
  1013.4     .06       0
Bank Sta=486.2,536.4
XS Rating Curve= 0 ,0
Exp/Cntr(USF)=0,0
Exp/Cntr=0.3,0.1
LCMann Table=0

Chan Stop Cuts=-1
Use User Specified Reach Order=0
Composite Channel Slope=5